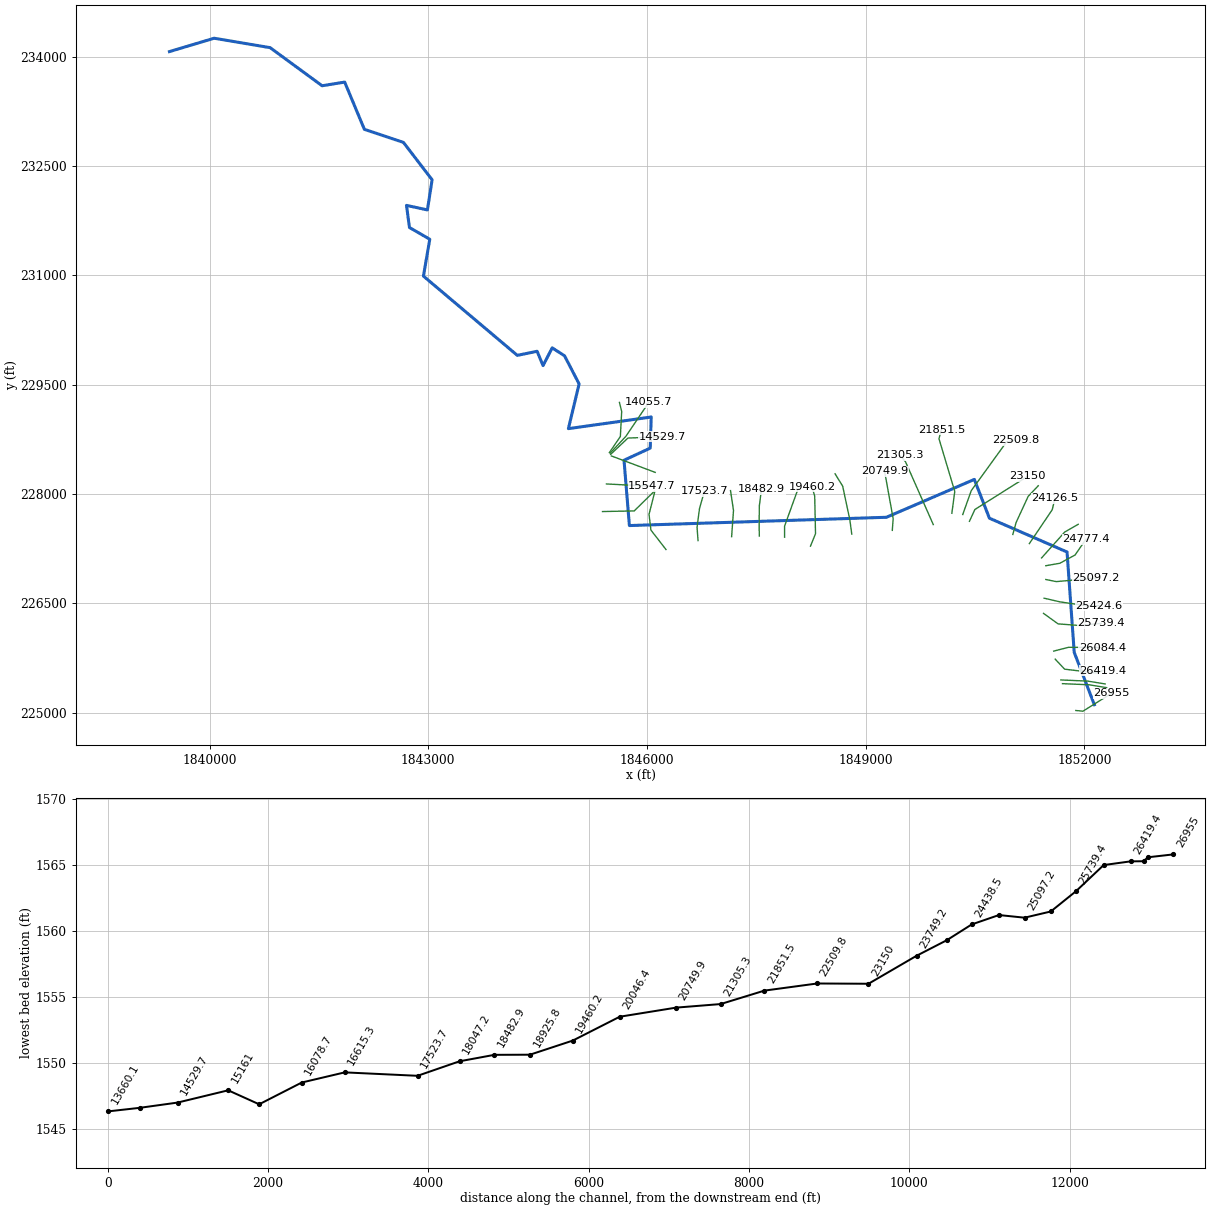
--- GALDECK.prj (project) ---

Proj Title=GALDECK
Current Plan=p01
Default Exp/Contr=0,0
English Units
Geom File=g01
Flow File=f01
Plan File=p01
BEGIN DESCRIPTION:
END DESCRIPTION:
DSS Export Rating Curves= 0
DSS Export Rating Curve Sorted= 0
DSS Export Volume Flow Curves= 0
DXF OffsetX= 0
DXF OffsetY= 0
DXF ScaleX= 0
DXF ScaleY= 0

--- GALDECK.p01 (plan) ---

Plan Title=Floodplain
Program Version=4.00
Geom File=g01
Flow File=f01
K Sum by GR=0
Std Step Tol=0.01
Critical Tol=0.01
Num of Std Step Trials=20
Max Error Tol=0.3
Flow Tol Ratio=0.001
Split Flow NTrial=30
Split Flow Tol=0.02
Split Flow Ratio=0.02
Log Output Level=0
Friction Slope Method=1
Unsteady Friction Slope Method=2
Unsteady Bridges Friction Slope Method=1
Global Log Level=0
CheckData=False
Run HTab=0
Run UNet=0
Run PostProcess=0
UNET Theta=0
UNET Theta Warmup=0
UNET ZTol=0
UNET ZSATol=0
UNET MxIter=0
UNET MaxInSteps=0
UNET DtIC=0
UNET DtMin=0
UNET MaxCRTS=0
UNET WFStab=0
UNET SFStab=0
UNET WFX=0
UNET SFX=0
UNET DSS MLevel=0
UNET DZMax Abort=0
UNET Convert EG Bridges=0
UNET Use Existing IB Tables=0
UNET Froude Limit=0
UNET Froude Power=0
Write IC File=0
Echo Input=False
Echo Output=False
Write Detailed=0

--- GALDECK.f01 (steady flow) ---

Flow Title=NFF Regression Equation
Program Version=4.00
Number of Profiles=1
Profile Names=P100yr
River Rch & RM=GALDECK,Main      ,26955
465.4374
River Rch & RM=GALDECK,Main      ,26636.1
669.1081
River Rch & RM=GALDECK,Main      ,25097.2
700.4033
River Rch & RM=GALDECK,Main      ,24126.5
771.5374
River Rch & RM=GALDECK,Main      ,21851.5
790.3454
River Rch & RM=GALDECK,Main      ,21305.3
1336.314
River Rch & RM=GALDECK,Main      ,18925.8
1396.246
River Rch & RM=GALDECK,Main      ,16078.7
1514.285
River Rch & RM=GALDECK,Main      ,7590.2
1655.643
River Rch & RM=GALDECK,Main      ,510.3
1832.542
River Rch & RM=GALDECK,Main      ,85.3
1832.949
Boundary for River Rch & Prof#=GALDECK,Main      ,1
Up Type=0
Dn Type=3
Dn Slope=0.001253

--- GALDECK.g01 (geometry) ---

Geom Title=USGS 10m DEM
Program Version=4.10

River Reach=GALDECK         ,Main
Reach XY= 30
     1852137.281      225107.735     1851861.165       225825.31
     1851762.462      227203.129     1850697.607      227666.866
     1850490.701      228198.832     1849285.419      227679.547
     1845759.238      227565.873     1845685.482      228462.042
     1846044.655      228628.373     1846058.662      229055.302
     1844922.432      228895.734     1845069.657      229508.882
     1844869.655      229895.039     1844700.225      230004.224
     1844574.843      229760.573     1844493.434      229957.139
     1844221.738      229901.289      1842934.08      230988.694
     1843020.923      231494.337     1842742.571      231655.456
     1842701.468      231959.197     1842988.599      231896.832
     1843052.988      232310.317     1842659.238      232823.511
     1842123.955      233002.593     1841853.839       233650.78
      1841543.96      233600.595     1840830.766      234123.511
      1840062.71      234252.678     1839450.627      234069.368

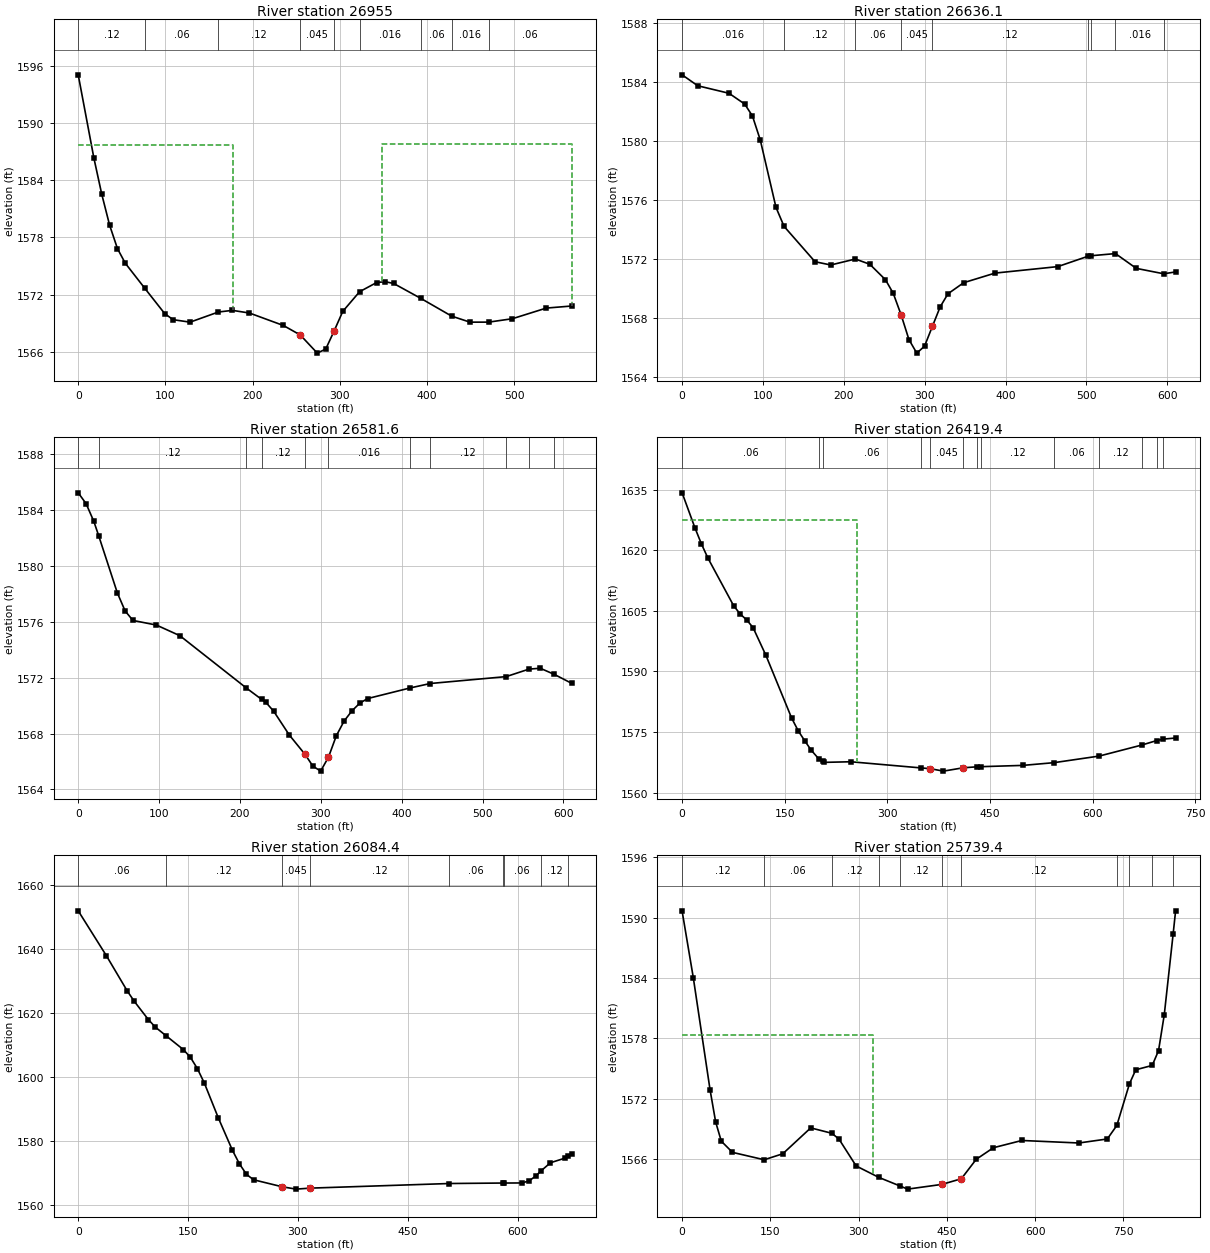
Type RM Length L Ch R = 1 ,26955   ,344.9,318.9,292
XS GIS Cut Line= 3
     1851882.354      225028.429     1851980.986      225018.949
     1852377.017      225266.345
#Sta/Elev= 30
       0 1595.12      18 1586.35      27 1582.55      36  1579.3      45 1576.83
      54 1575.29   76.541572.632    99.1    1570   108.8 1569.35   128.3 1569.09
  160.741570.157   176.9 1570.33   196.4 1570.05   235.3 1568.74   254.7 1567.74
   274.2 1565.83   283.9 1566.26   293.6 1568.18   303.4 1570.22  322.731572.294
   342.3 1573.26     352 1573.35   361.8 1573.16  393.121571.582  428.311569.724
   449.3 1569.09  470.721569.092   497.9 1569.45   536.8 1570.57     566 1570.79
#Mann= 9 ,-1 , 0
       0     .12       0   76.54     .06       0  160.74     .12       0
   254.7    .045       0   293.6     .06       0  322.73    .016       0
  393.12     .06       0  428.31    .016       0  470.72     .06       0
#XS Ineff= 2 , 0
          177.81 1587.77   348.8         1587.81
Permanent Ineff=
       F       F
Bank Sta=254.7,293.6
XS Rating Curve= 0 ,0
Exp/Cntr=0.3,0.1

Type RM Length L Ch R = 1 ,26636.1 ,77,54.5,56.3
XS GIS Cut Line= 3
     1851699.933      225396.554     1852067.121      225380.929
     1852306.704      225341.866
#Sta/Elev= 30
       0 1584.46    19.3 1583.72      58 1583.21    77.4 1582.48      87 1581.67
    96.7 1580.04   116.1 1575.48  126.081574.195   164.4  1571.8   183.8 1571.58
  214.281571.984   232.1 1571.63   251.5 1570.58   261.1 1569.66   270.8 1568.21
   280.5 1566.53   290.2 1565.61   299.8 1566.08   309.5 1567.42   319.2 1568.75
   328.8 1569.63   348.2 1570.38   386.9 1571.03   464.6 1571.47  501.441572.162
  506.071572.208  535.921572.352   561.7 1571.35  595.621570.984   610.3 1571.11
#Mann= 9 ,-1 , 0
       0    .016       0  126.08     .12       0  214.28     .06       0
   270.8    .045       0   309.5     .12       0  501.44     .06       0
  506.07     .08       0  535.92    .016       0  595.62     .12       0
Bank Sta=270.8,309.5
XS Rating Curve= 0 ,0
Exp/Cntr=0.3,0.1

Type RM Length L Ch R = 1 ,26581.6 ,140.9,162.1,159
XS GIS Cut Line= 3
     1851677.798      225447.335     1852044.986       225431.71
     1852284.569      225392.647
#Sta/Elev= 30
       0 1585.22     9.7 1584.45    19.3 1583.18   25.371582.141    48.4 1578.06
      58 1576.77    67.7 1576.09    96.7 1575.76   125.7    1575   208.11571.248
  226.931570.438   232.1 1570.23   241.8 1569.59   261.1 1567.89   280.5 1566.51
   290.2 1565.67   299.8 1565.31   309.5 1566.31   319.2 1567.84   328.8 1568.89
   338.5 1569.62   348.2 1570.17   357.8  1570.5   409.91571.253  435.441571.579
  529.291572.072  557.461572.608   571.4 1572.67  588.991572.225   610.3 1571.59
#Mann= 11 ,-1 , 0
       0      .1       0   25.37     .12       0   208.1     .06       0
  226.93     .12       0   280.5    .045       0   309.5    .016       0
   409.9     .06       0  435.44     .12       0  529.29     .06       0
  557.46    .016       0  588.99     .06       0
Bank Sta=280.5,309.5
XS Rating Curve= 0 ,0
Exp/Cntr=0.3,0.1

Type RM Length L Ch R = 1 ,26419.4 ,331.3,335,338.4
XS GIS Cut Line= 4
     1851600.294      225732.666     1851729.447      225595.338
     1852161.739      225543.255     1852253.731      225575.806
#Sta/Elev= 30
       0  1634.2    18.8 1625.51    28.3 1621.52    37.7 1618.05    75.4 1606.23
    84.8 1604.22    94.3 1602.75   103.7 1600.84   122.5 1593.97   160.2 1578.41
   169.7  1575.3   179.1 1572.86   188.5 1570.54  200.291568.231   205.6  1567.7
   207.9 1567.47   246.6 1567.62  349.741566.087   362.7 1565.91     382  1565.3
   411.1 1566.13  430.851566.363  437.641566.405   498.2 1566.72  543.771567.396
  609.971569.034  672.151571.763  693.811572.864  703.671573.227   721.5  1573.5
#Mann= 13 ,-1 , 0
       0     .06       0  200.29     .12       0   205.6     .06       0
  349.74     .12       0   362.7    .045       0   411.1     .12       0
  430.85     .06       0  437.64     .12       0  543.77     .06       0
  609.97     .12       0  672.15    .016       0  693.81     .06       0
  703.67    .016       0
#XS Ineff= 2 , 0
          255.23 1627.45
Permanent Ineff=
       F       F
Bank Sta=362.7,411.1
XS Rating Curve= 0 ,0
Exp/Cntr=0.3,0.1

Type RM Length L Ch R = 1 ,26084.4 ,339.2,345,325.6
XS GIS Cut Line= 3
     1851579.491      225843.342     1851783.484      225895.425
     1852246.808      225892.417
#Sta/Elev= 30
       0 1651.91    38.3 1637.96      67 1626.88    76.6 1623.64    95.7 1617.98
   105.3  1615.6  119.551612.983   143.6 1608.58   153.1 1606.21   162.7 1602.66
   172.3  1598.1   191.4 1587.22   210.5 1577.19   220.2 1572.89   229.8 1569.63
   239.5 1567.94   278.1 1565.78   297.4 1565.02   316.7 1565.33  506.961566.772
  580.011566.922  580.821566.919   606.3 1566.95     616 1567.63   625.6 1569.27
  631.331570.581   644.9 1573.26   664.2 1574.66  669.321575.404   673.9 1576.07
#Mann= 9 ,-1 , 0
       0     .06       0  119.55     .12       0   278.1    .045       0
   316.7     .12       0  506.96     .06       0  580.01     .12       0
  580.82     .06       0  631.33     .12       0  669.32    .016       0
Bank Sta=278.1,316.7
XS Rating Curve= 0 ,0
Exp/Cntr=0.3,0.1

Type RM Length L Ch R = 1 ,25739.4 ,317.4,314.8,309
XS GIS Cut Line= 4
     1851439.668      226361.028     1851640.255      226216.606
     1851931.053      226194.904     1852229.672      226224.042
#Sta/Elev= 30
       0 1590.64      19 1584.04    47.5  1572.9      57 1569.71    66.6  1567.8
    85.6 1566.69   139.51565.956   171.1 1566.55   218.6 1569.12   254.51568.585
   266.6 1568.01   295.8 1565.34  334.461564.203  370.931563.339   383.2 1563.04
   441.6 1563.51   474.6 1564.07   499.9    1566   529.1 1567.15   577.5 1567.87
   674.3 1567.62   722.7 1568.02  738.871569.359  760.381573.502   771.1 1574.89
  799.061575.321   809.8 1576.79   819.5 1580.34  834.561588.345   838.8 1590.67
#Mann= 11 ,-1 , 0
       0     .12       0   139.5     .06       0   254.5     .12       0
  334.46     .06       0  370.93     .12       0   441.6    .045       0
   474.6     .12       0  738.87     .06       0  760.38     .12       0
  799.06    .016       0  834.56     .12       0
#XS Ineff= 2 , 0
          324.09 1578.35
Permanent Ineff=
       F       F
Bank Sta=441.6,474.6
XS Rating Curve= 0 ,0
Exp/Cntr=0.3,0.1

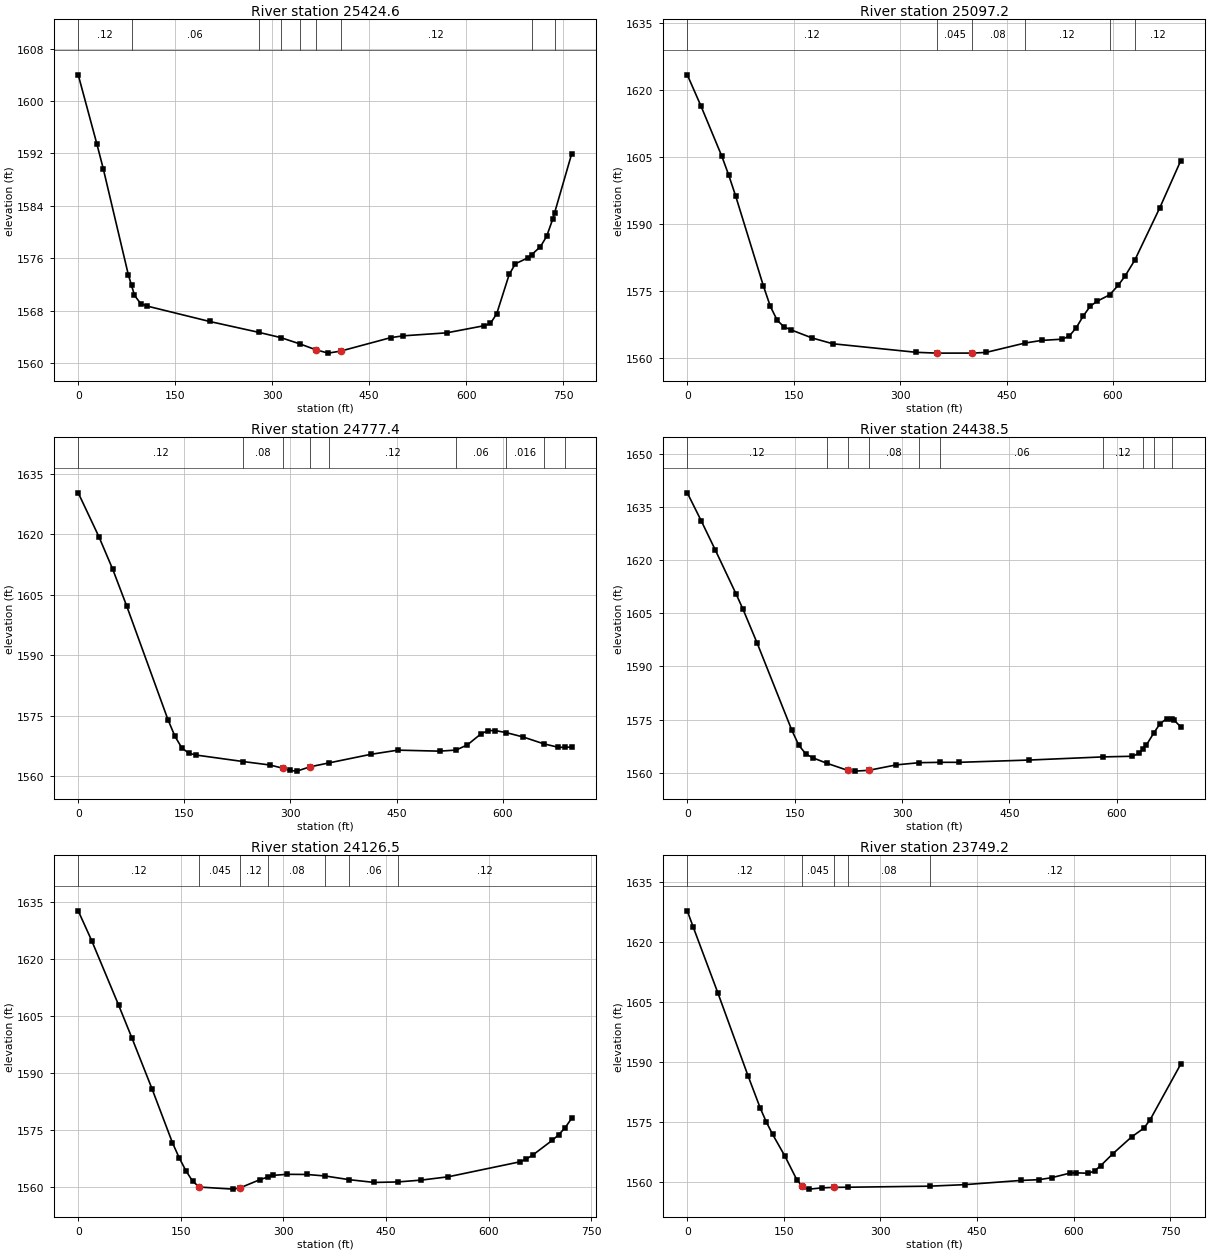
Type RM Length L Ch R = 1 ,25424.6 ,318.3,327.4,336.2
XS GIS Cut Line= 4
     1851448.576        226569.2     1851665.211       226518.95
     1852066.253      226459.922     1852201.182       226468.58
#Sta/Elev= 30
       0 1604.01      29 1593.39    38.7 1589.68    77.4 1573.51   82.461571.839
      87 1570.34    96.7 1569.04   106.4 1568.69     203 1566.34  279.281564.672
  312.781563.884     3431562.902   367.2 1562.02   386.5  1561.5   405.8 1561.81
     483 1563.86   502.3 1564.14   569.8  1564.6   627.8 1565.69   637.4 1566.03
   647.1 1567.52   666.4 1573.52     676 1575.15   695.4 1576.06  701.011576.527
   714.7 1577.76   724.3 1579.34     734 1582.05  736.651582.953     763 1591.94
#Mann= 9 ,-1 , 0
       0     .12       0   82.46     .06       0  279.28     .12       0
  312.78     .06       0     343     .12       0   367.2    .045       0
   405.8     .12       0  701.01    .016       0  736.65     .12       0
Bank Sta=367.2,405.8
XS Rating Curve= 0 ,0
Exp/Cntr=0.3,0.1

Type RM Length L Ch R = 1 ,25097.2 ,299.9,319.7,334.8
XS GIS Cut Line= 3
     1851471.496      226825.677     1851614.864      226796.727
     1852161.769      226846.321
#Sta/Elev= 30
       0 1623.42    19.5 1616.35    48.8 1605.12    58.5 1600.89    68.3 1596.19
   107.3 1576.07     117 1571.53   126.8 1568.37   136.5  1566.9   146.3 1566.24
   175.7 1564.44   205.1 1563.13   322.8 1561.21   352.2 1561.03   401.2 1561.04
   420.8 1561.18  475.421563.275   499.3 1563.88   528.7 1564.16   538.5 1564.88
   548.3 1566.77   558.1 1569.37   567.9 1571.56   577.7 1572.67  595.231574.106
   607.2 1576.22     617 1578.32  630.751581.905     666 1593.66   695.4 1604.17
#Mann= 6 ,-1 , 0
       0     .12       0   352.2    .045       0   401.2     .08       0
  475.42     .12       0  595.23    .016       0  630.75     .12       0
Bank Sta=352.2,401.2
XS Rating Curve= 0 ,0
Exp/Cntr=0.3,0.1

Type RM Length L Ch R = 1 ,24777.4 ,313.3,338.9,348.1
XS GIS Cut Line= 4
      1851471.18      227014.777     1851663.475      227048.463
     1851871.808      227161.311     1852023.031      227379.306
#Sta/Elev= 30
       0 1630.33    29.3 1619.41    48.8 1611.34    68.3 1602.34   126.9 1573.99
   136.7 1569.89   146.4 1567.01   156.2 1565.69   165.9 1565.24  233.061563.611
     271 1562.75     290 1561.92   299.5 1561.39     309 1561.23   327.9 1562.31
  354.911563.287   413.2 1565.39   451.8 1566.44   510.8 1566.19  534.061566.458
   550.1 1567.75   569.7 1570.54   579.6 1571.29   589.4  1571.3  604.841570.797
   628.7 1569.72  657.931568.015   677.8 1567.18  688.511567.113   697.5 1567.24
#Mann= 9 ,-1 , 0
       0     .12       0  233.06     .08       0     290    .045       0
   327.9     .08       0  354.91     .12       0  534.06     .06       0
  604.84    .016       0  657.93     .06       0  688.51     .12       0
Bank Sta=290,327.9
XS Rating Curve= 0 ,0
Exp/Cntr=0.3,0.1

Type RM Length L Ch R = 1 ,24438.5 ,301.4,312,310
XS GIS Cut Line= 3
     1851412.966      227121.532     1851731.183      227477.283
     1851914.993      227582.819
#Sta/Elev= 30
       0 1638.93    19.5 1631.03      39 1622.88    68.2 1610.42    77.9  1606.1
    97.4 1596.69   146.1 1572.01   155.8 1567.81   165.6 1565.36   175.3 1564.27
  194.751562.754     224 1560.74   233.8 1560.52   253.3 1560.74   292.2 1562.29
  324.351562.901  353.69    1563   379.9    1563   477.3 1563.64  581.091564.531
   621.8 1564.71   631.4 1565.56  636.171566.662   641.1  1567.8  651.661571.268
   660.4 1573.89     670 1575.34  676.641575.084   679.6 1574.97   689.3 1572.98
#Mann= 10 ,-1 , 0
       0     .12       0  194.75     .08       0     224    .045       0
   253.3     .08       0  324.35     .12       0  353.69     .06       0
  581.09     .12       0  636.17     .06       0  651.66     .12       0
  676.64    .016       0
Bank Sta=224,253.3
XS Rating Curve= 0 ,0
Exp/Cntr=0.3,0.1

Type RM Length L Ch R = 1 ,24126.5 ,351.4,377.3,372.6
XS GIS Cut Line= 3
     1851245.195      227318.438     1851559.308      227782.838
       1851597.2      227939.057
#Sta/Elev= 30
       0 1632.59    19.7 1624.74      59  1607.8    78.7 1599.03   108.2 1585.59
   137.7 1571.56   147.5 1567.61   157.4 1564.17   167.2 1561.42     177 1559.87
   226.2 1559.32   236.1 1559.62   265.6 1561.81  277.811562.548   285.2 1562.94
   304.9 1563.22   334.4 1563.18  361.311562.773  396.571561.798   432.8 1561.08
  467.291561.211   501.6  1561.7     541 1562.57   645.8 1566.51   655.2 1567.24
   664.7 1568.32     693 1572.17   702.5 1573.64     712 1575.54   721.4 1577.96
#Mann= 7 ,-1 , 0
       0     .12       0     177    .045       0   236.1     .12       0
  277.81     .08       0  361.31     .12       0  396.57     .06       0
  467.29     .12       0
Bank Sta=177,236.1
XS Rating Curve= 0 ,0
Exp/Cntr=0.3,0.1

Type RM Length L Ch R = 1 ,23749.2 ,624.2,599.2,576.1
XS GIS Cut Line= 4
     1851018.769      227443.761     1851063.553      227607.937
     1851229.447      227966.866     1851367.816      228112.196
#Sta/Elev= 30
       0 1627.83     9.4 1623.68    47.3 1607.36    94.5 1586.44   113.4 1578.39
   122.9  1574.9   132.4 1571.88   151.3 1566.49   170.2 1560.46   177.8 1558.98
   179.8 1558.59   189.5 1558.14   208.8 1558.45     228 1558.59  248.961558.613
  376.291558.879   430.6 1559.26   517.4 1560.31   546.3 1560.51   565.6    1561
   594.2 1562.15   603.8 1562.22   622.9 1562.11   632.5 1562.72     642 1564.03
   661.1 1567.05   689.8  1571.2   708.9  1573.4   718.5 1575.47   766.2 1589.44
#Mann= 5 ,-1 , 0
       0     .12       0   177.8    .045       0     228     .12       0
  248.96     .08       0  376.29     .12       0
Bank Sta=177.8,228
XS Rating Curve= 0 ,0
Exp/Cntr=0.3,0.1

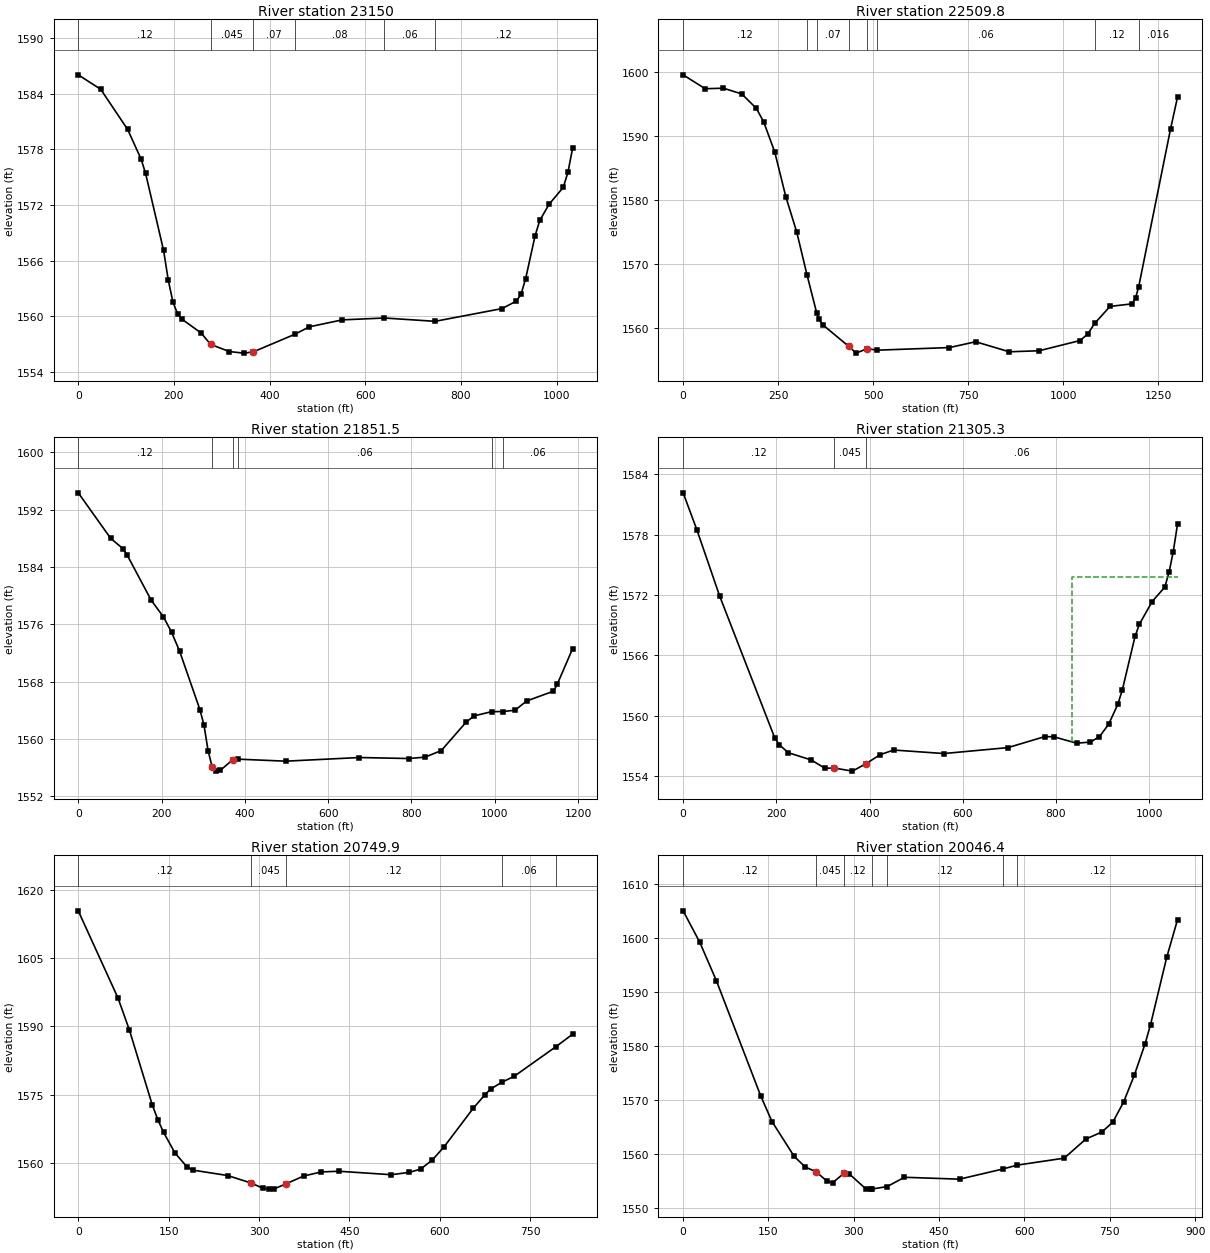
Type RM Length L Ch R = 1 ,23150   ,372.6,640.2,503.2
XS GIS Cut Line= 3
     1850423.739      227624.395     1850498.545      227786.311
     1851222.318      228242.166
#Sta/Elev= 30
       0 1586.06    46.9  1584.5   103.3 1580.16   131.4 1576.96   140.8 1575.42
   178.4 1567.11   188.2  1563.9     198 1561.53   207.9 1560.23   217.7 1559.65
     257 1558.19   276.7 1556.96     316 1556.19   345.5 1556.02   365.2 1556.14
     4531558.058   483.2 1558.86     552 1559.61  640.231559.811  746.061559.452
   886.2 1560.83   915.8 1561.63   925.6 1562.35   935.4 1564.05   955.1 1568.67
   964.9 1570.34   984.6  1572.1  1014.1 1573.91  1023.9 1575.55  1033.7 1578.16
#Mann= 6 ,-1 , 0
       0     .12       0   276.7    .045       0   365.2     .07       0
     453     .08       0  640.23     .06       0  746.06     .12       0
Bank Sta=276.7,365.2
XS Rating Curve= 0 ,0
Exp/Cntr=0.3,0.1

Type RM Length L Ch R = 1 ,22509.8 ,371.8,658.3,503.1
XS GIS Cut Line= 4
     1850331.905      227717.485     1850448.197      228044.557
     1850932.138       228712.96     1851058.172      228737.753
#Sta/Elev= 30
       0 1599.52    57.9 1597.35   106.1 1597.43   154.3 1596.53   192.8 1594.27
   212.1 1592.14   241.1 1587.45     270 1580.51   298.9 1574.95  326.071568.241
  351.12 1562.38     357 1561.37   366.8  1560.5   435.6  1557.1   455.2 1556.04
   484.7 1556.75  509.621556.499   700.8 1556.91   769.6 1557.82     858 1556.25
   936.6 1556.41  1044.6 1558.01  1064.3 1559.01 1082.76 1560.68  1123.2 1563.34
  1181.5 1563.74  1190.7 1564.73 1198.431566.352  1282.4 1591.05  1300.8 1596.04
#Mann= 8 ,-1 , 0
       0     .12       0  326.07     .06       0  351.12     .07       0
   435.6    .045       0   484.7     .07       0  509.62     .06       0
 1082.76     .12       0 1198.43    .016       0
Bank Sta=435.6,484.7
XS Rating Curve= 0 ,0
Exp/Cntr=0.3,0.1

Type RM Length L Ch R = 1 ,21851.5 ,533.6,546.3,544.3
XS GIS Cut Line= 4
     1850182.383      227734.493     1850222.503      228033.706
     1850005.489      228758.533     1850040.085      228882.502
#Sta/Elev= 30
       0 1594.36    77.9    1588   107.1 1586.58   116.9 1585.73   175.3 1579.35
   204.5 1577.04     224 1574.91   243.5 1572.23   292.2 1564.07   301.9 1561.94
   311.7 1558.37   321.5 1556.09   331.4  1555.5   341.2 1555.61   370.7 1557.08
  383.82 1557.17   498.4 1556.89   675.3  1557.4   793.2 1557.26   832.5 1557.45
   871.8 1558.37   930.8  1562.3   950.4 1563.21  992.781563.806 1019.23 1563.82
  1048.7    1564  1076.9  1565.3  1141.2 1566.66  1150.4 1567.65  1187.2 1572.61
#Mann= 6 ,-1 , 0
       0     .12       0   321.5    .045       0   370.7     .12       0
  383.82     .06       0  992.78    .016       0 1019.23     .06       0
Bank Sta=321.5,370.7
XS Rating Curve= 0 ,0
Exp/Cntr=0.3,0.1

Type RM Length L Ch R = 1 ,21305.3 ,550.6,555.4,539.5
XS GIS Cut Line= 3
       1849927.5      227579.399     1849546.722      228441.259
     1849468.881      228530.398
#Sta/Elev= 30
       0 1582.17    29.4  1578.5    78.5 1571.88   196.3 1557.81   206.1 1557.11
   225.7 1556.31   274.8 1555.59   304.3 1554.76   323.9 1554.79   363.2 1554.48
   392.6 1555.23     422  1556.1   451.5 1556.58   559.4 1556.23   696.9 1556.82
   775.4 1557.91     795  1557.9   844.1 1557.26   873.5 1557.37   893.2 1557.91
   912.8 1559.14   932.4 1561.11   942.2 1562.56   969.5 1567.89   978.6 1569.08
    1006 1571.34  1033.3 1572.79  1042.4 1574.26  1051.5 1576.33  1060.6 1579.06
#Mann= 3 ,-1 , 0
       0     .12       0   323.9    .045       0   392.6     .06       0
#XS Ineff= 2 , 0
                           833.8         1573.75
Permanent Ineff=
       F       F
Bank Sta=323.9,392.6
XS Rating Curve= 0 ,0
Exp/Cntr=0.3,0.1

Type RM Length L Ch R = 1 ,20749.9 ,701.9,703.5,697.6
XS GIS Cut Line= 3
     1849365.662       227499.88     1849377.451      227660.009
     1849260.065      228309.419
#Sta/Elev= 30
       0 1615.37    66.1 1596.16      85 1589.12   122.8 1572.73   132.2 1569.43
   141.7 1566.66   160.6 1562.14     180 1559.17   189.7  1558.4   247.9  1557.2
   286.7 1555.56   306.1 1554.43   315.8 1554.21   325.5 1554.28     345 1555.39
   374.1 1557.09   403.2 1557.99   432.3 1558.14   519.6 1557.38   548.8 1557.88
   568.2 1558.61   587.6 1560.61     607 1563.49   655.5 1571.97   674.9 1574.95
   684.6 1576.22  702.771577.681   723.4    1579  792.631585.502   820.5 1588.26
#Mann= 5 ,-1 , 0
       0     .12       0   286.7    .045       0     345     .12       0
  702.77     .06       0  792.63     .12       0
Bank Sta=286.7,345
XS Rating Curve= 0 ,0
Exp/Cntr=0.3,0.1

Type RM Length L Ch R = 1 ,20046.4 ,569.5,586.1,558.5
XS GIS Cut Line= 4
     1848809.369      227448.198     1848783.701      227641.779
     1848685.013      228105.975     1848580.919      228275.757
#Sta/Elev= 30
       0 1604.95    29.3 1599.12    58.6    1592   136.7 1570.66   156.2 1566.01
   195.3 1559.55   214.6 1557.62     234 1556.69   253.4 1554.95   263.1 1554.73
   282.4 1556.42   292.1 1556.33   321.2 1553.56   330.9 1553.52  331.541553.524
  358.69    1554     389 1555.71   485.8 1555.36  562.041557.241  587.381557.961
   669.8 1559.24   707.8 1562.77   736.2 1564.09   755.2 1565.89   774.2 1569.61
   793.1 1574.58   812.1 1580.41   821.6 1583.93     850 1596.35     869 1603.31
#Mann= 7 ,-1 , 0
       0     .12       0     234    .045       0   282.4     .12       0
  331.54     .06       0  358.69     .12       0  562.04     .06       0
  587.38     .12       0
Bank Sta=234,282.4
XS Rating Curve= 0 ,0
Exp/Cntr=0.3,0.1

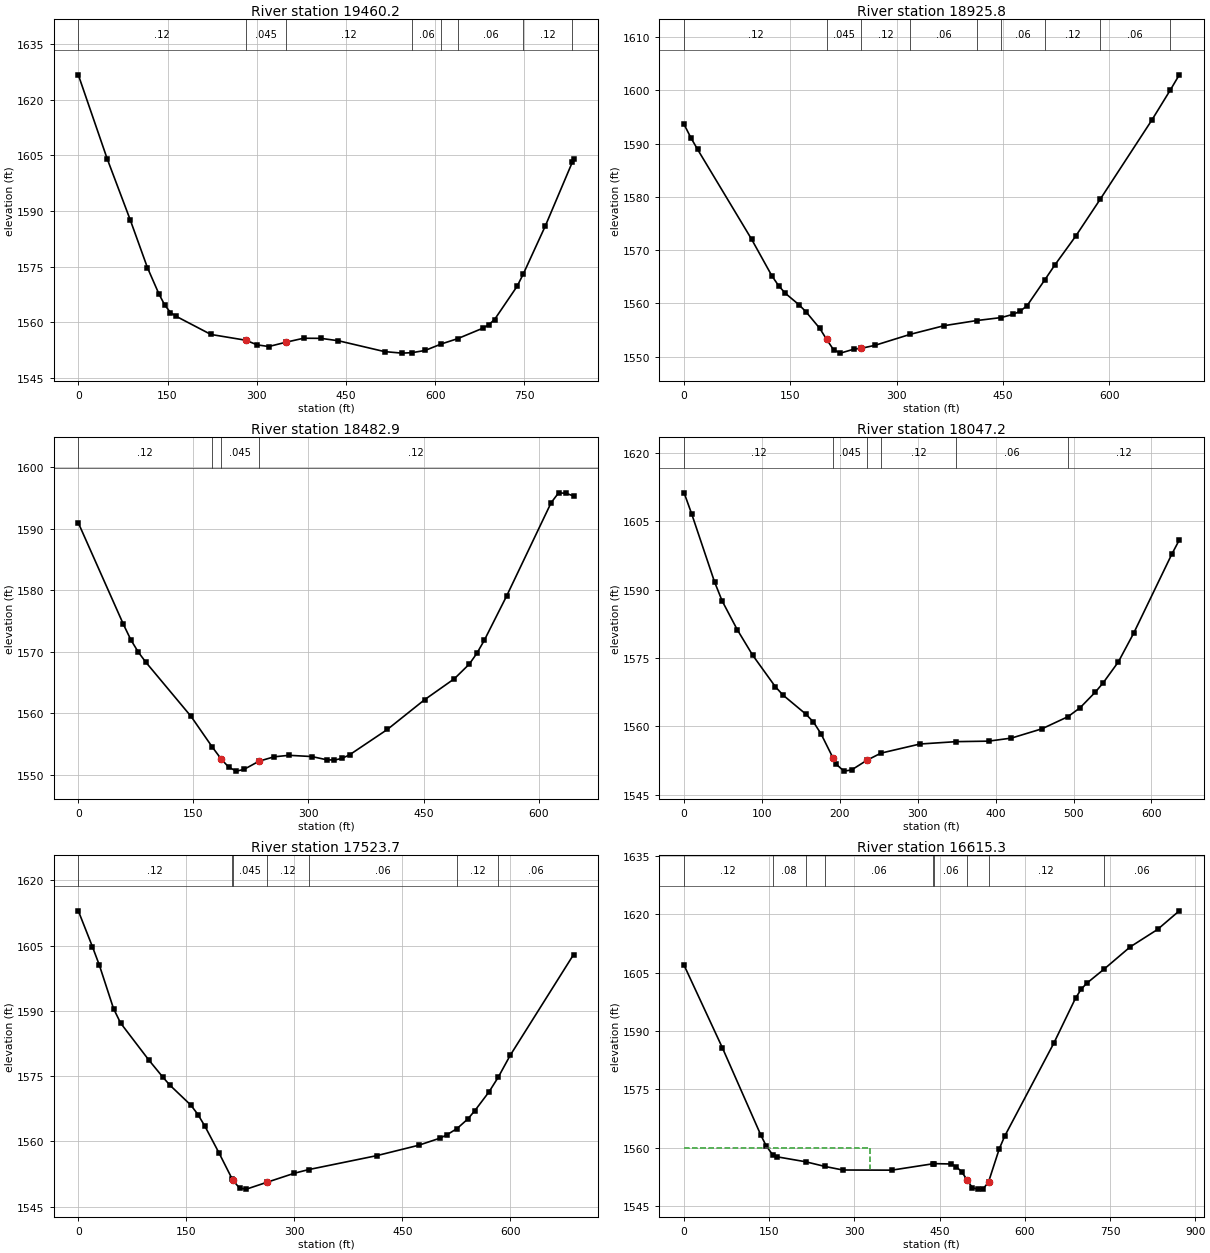
Type RM Length L Ch R = 1 ,19460.2 ,507.8,534.4,508.8
XS GIS Cut Line= 4
     1848243.178      227283.794     1848312.347      227454.279
     1848301.015      227969.884     1848264.075      228097.281
#Sta/Elev= 30
       0 1626.69    48.4 1604.14    87.2 1587.65   116.2 1574.74   135.6 1567.63
   145.2 1564.69   154.9 1562.65   164.6 1561.62   222.9 1556.74   281.3 1555.19
   300.8 1553.93   320.2 1553.49   349.4 1554.66   378.6 1555.72   407.8 1555.69
     437 1555.05   514.8 1552.12     544 1551.71  560.831551.828   582.9 1552.43
  610.321554.185  637.591555.605   680.2 1558.44     690 1559.38   699.7 1560.77
   737.6 1569.72  748.181573.105     785 1585.97  830.441603.174   832.4  1603.9
#Mann= 8 ,-1 , 0
       0     .12       0   281.3    .045       0   349.4     .12       0
  560.83     .06       0  610.32     .12       0  637.59     .06       0
  748.18     .12       0  830.44     .06       0
Bank Sta=281.3,349.4
XS Rating Curve= 0 ,0
Exp/Cntr=0.3,0.1

Type RM Length L Ch R = 1 ,18925.8 ,427.4,442.9,464.1
XS GIS Cut Line= 3
     1847887.867      227406.069     1847887.867      227558.446
     1848073.935      228072.347
#Sta/Elev= 30
       0  1593.6     9.5 1591.12      19 1588.92    95.2 1572.05   123.8 1565.18
   133.3 1563.32   142.8 1561.89   162.1 1559.73   171.9 1558.43   191.4  1555.3
   201.2 1553.21   210.9 1551.28   220.7 1550.64   240.2 1551.41     250 1551.54
   269.5 1552.11  319.391554.179   367.1  1555.8  412.681556.754  447.561557.321
   464.7 1557.94   474.4 1558.52   484.2 1559.58  509.361564.463   523.2 1567.19
   552.5 1572.58   587.3 1579.55   659.9 1594.37  686.251600.074   698.9 1602.92
#Mann= 9 ,-1 , 0
       0     .12       0   201.2    .045       0     250     .12       0
  319.39     .06       0  412.68     .12       0  447.56     .06       0
  509.36     .12       0   587.3     .06       0  686.25     .12       0
Bank Sta=201.2,250
XS Rating Curve= 0 ,0
Exp/Cntr=0.3,0.1

Type RM Length L Ch R = 1 ,18482.9 ,428.9,435.7,418.3
XS GIS Cut Line= 4
     1847541.571      227421.936     1847538.909      227568.863
     1847541.513      227834.488     1847570.787      228065.594
#Sta/Elev= 30
       0 1590.99    58.8 1574.49    68.6 1571.95    78.4 1569.94    88.2 1568.31
     147 1559.52   174.81554.519   186.3 1552.59   196.1 1551.27     206 1550.63
   215.8  1550.9   235.5 1552.24   255.2 1552.96   274.8  1553.2   304.4    1553
     324 1552.47   333.9 1552.43   343.7  1552.7   353.6 1553.28   402.8  1557.4
   451.4 1562.24   490.2 1565.65   509.6 1568.02   519.4 1569.76   529.1 1571.87
   558.2 1579.07   616.4 1594.28   626.1 1595.87   635.8 1595.79   645.5 1595.36
#Mann= 4 ,-1 , 0
       0     .12       0   174.8     .08       0   186.3    .045       0
   235.5     .12       0
Bank Sta=186.3,235.5
XS Rating Curve= 0 ,0
Exp/Cntr=0.3,0.1

Type RM Length L Ch R = 1 ,18047.2 ,524.7,523.5,520
XS GIS Cut Line= 3
     1847161.462      227414.061     1847187.347      227774.592
     1847146.087       228045.73
#Sta/Elev= 30
       0 1611.22     9.8 1606.57    39.1 1591.66    48.8 1587.51    68.4 1581.14
    87.9 1575.62   117.2 1568.65     127 1566.83   156.3 1562.65   166.1 1560.91
   175.8 1558.32  190.991553.089   195.4 1551.64   205.2 1550.14   214.9 1550.39
   234.5 1552.51  252.671554.089   302.8 1556.09  349.25 1556.61   390.8 1556.72
   420.2 1557.39   459.4 1559.43  492.831562.094   508.4 1564.06     528  1567.5
   537.8 1569.48   557.4  1574.1     577 1580.37   625.9  1597.7   635.7 1600.88
#Mann= 6 ,-1 , 0
       0     .12       0  190.99    .045       0   234.5     .08       0
  252.67     .12       0  349.25     .06       0  492.83     .12       0
Bank Sta=190.99,234.5
XS Rating Curve= 0 ,0
Exp/Cntr=0.3,0.1

Type RM Length L Ch R = 1 ,17523.7 ,781.3,908.3,880.2
XS GIS Cut Line= 4
      1846700.68      227360.091     1846687.347      227545.425
     1846721.201      227800.634     1846787.816      228035.913
#Sta/Elev= 30
       0 1613.02    19.6 1604.78    29.3  1600.5    48.9 1590.56    58.7 1587.23
    97.8 1578.75   117.4 1574.79   127.1 1572.96   156.5 1568.32   166.2 1566.18
     176 1563.46   195.4 1557.37  213.541551.418   214.4 1551.14     224 1549.27
   233.5 1549.04   262.1 1550.62   300.2  1552.7  320.071553.536   414.6 1556.74
   472.6 1559.12   501.9 1560.73   511.7  1561.5  526.111562.974   541.1 1565.18
   550.8 1567.09   570.4 1571.39   583.41574.807   599.8 1579.78   687.8 1602.94
#Mann= 7 ,-1 , 0
       0     .12       0  213.54     .08       0   214.4    .045       0
   262.1     .12       0  320.07     .06       0  526.11     .12       0
   583.4     .06       0
Bank Sta=214.4,262.1
XS Rating Curve= 0 ,0
Exp/Cntr=0.3,0.1

Type RM Length L Ch R = 1 ,16615.3 ,602.3,536.6,540
XS GIS Cut Line= 4
     1846261.138      227237.116     1846054.534      227503.759
     1846028.492      227719.904     1846106.617      228027.196
#Sta/Elev= 30
       0 1606.89    67.5 1585.64   134.9 1563.28   144.6 1560.42  155.841558.174
   163.8 1557.61  214.021556.341   248.21555.129   279.5 1554.22   365.7 1554.18
  437.731555.812  440.061555.861   469.8 1555.77   479.3 1555.09   488.8 1553.76
   498.2 1551.73   507.7 1549.64   517.2  1549.3   526.6 1549.36   536.1 1551.12
     555 1559.65   564.6 1562.93   651.1 1586.85   689.5 1598.47   699.2 1600.71
   708.8 1602.23  739.661605.905   785.6 1611.62   833.7  1616.1   872.1  1620.9
#Mann= 9 ,-1 , 0
       0     .12       0  155.84     .08       0  214.02     .12       0
   248.2     .06       0  437.73     .12       0  440.06     .06       0
   498.2    .045       0   536.1     .12       0  739.66     .06       0
#XS Ineff= 2 , 0
       0   327.7    1560               0
Permanent Ineff=
       F       F
Bank Sta=498.2,536.1
XS Rating Curve= 0 ,0
Exp/Cntr=0.3,0.1

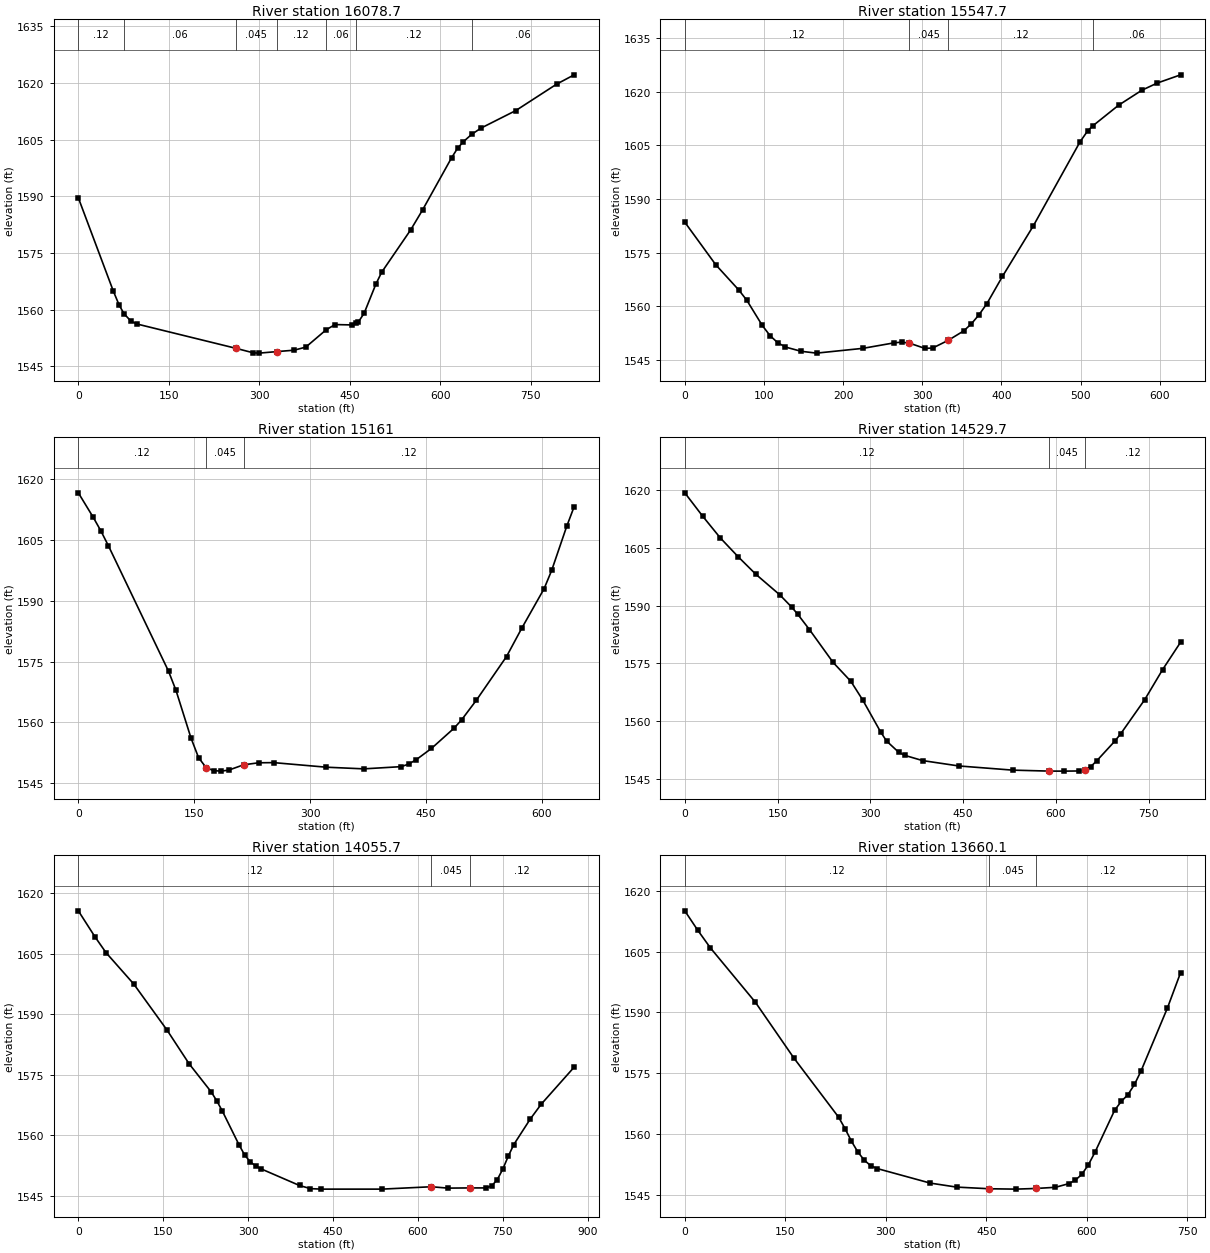
Type RM Length L Ch R = 1 ,16078.7 ,450.5,531,406.3
XS GIS Cut Line= 3
     1845390.526      227758.048     1845825.367      227766.779
     1846101.409      228037.613
#Sta/Elev= 30
       0 1589.64      58 1564.94    67.7 1561.22   75.751558.956      87 1557.02
    96.6 1556.26  260.771549.818     290 1548.61   299.6 1548.53   328.6 1548.93
   357.6 1549.31   376.9 1550.12  410.541554.689   425.3 1556.09   454.3 1555.99
  459.661556.414   463.9 1556.75   473.6 1559.09   492.9 1566.74   502.6 1569.93
   550.9  1581.2   570.3  1586.4   618.6 1600.27   628.3 1602.72     638 1604.49
  651.721606.425     667 1608.07     725 1612.74   792.6 1619.73   821.6 1622.19
#Mann= 7 ,-1 , 0
       0     .12       0   75.75     .06       0  260.77    .045       0
   328.6     .12       0  410.54     .06       0  459.66     .12       0
  651.72     .06       0
Bank Sta=260.77,328.6
XS Rating Curve= 0 ,0
Exp/Cntr=0.3,0.1

Type RM Length L Ch R = 1 ,15547.7 ,378.9,386.7,365.2
XS GIS Cut Line= 2
     1845444.524      228136.603     1846070.159      228105.321
#Sta/Elev= 30
       0 1583.51    39.2 1571.58    68.5 1564.47    78.3 1561.68    97.9 1554.62
   107.7 1551.77   117.4 1549.79   127.2 1548.58   146.8  1547.4   166.4 1546.88
   225.1 1548.22   264.3 1549.75   274.1 1549.96   283.8 1549.67   303.4  1548.2
   313.2 1548.31   332.8 1550.46   352.4  1553.1   362.2 1555.11   371.9 1557.67
   381.7 1560.74   401.3 1568.34   440.4 1582.52   499.2 1605.95     509 1609.07
  515.271610.433   548.1 1616.25   577.5 1620.44     597 1622.45   626.4 1624.74
#Mann= 4 ,-1 , 0
       0     .12       0   283.8    .045       0   332.8     .12       0
  515.27     .06       0
Bank Sta=283.8,332.8
XS Rating Curve= 0 ,0
Exp/Cntr=0.3,0.1

Type RM Length L Ch R = 1 ,15161   ,558.8,631.3,643.3
XS GIS Cut Line= 2
      1845512.44      228521.172     1846113.305      228295.847
#Sta/Elev= 30
       0 1616.65    19.4 1610.57    29.2 1607.24    38.9 1603.59   116.7 1572.62
   126.4 1567.87   145.8 1556.12   155.6 1551.27   165.3 1548.83     175 1548.06
   184.7 1547.94   194.5 1548.18   213.9  1549.5   233.4    1550   252.8 1550.04
   320.9 1548.91   369.5  1548.5   418.1 1549.05   427.8 1549.71   437.5 1550.79
     457 1553.54   486.2 1558.53   495.9 1560.57   515.3 1565.49   554.2 1576.24
   573.7 1583.16   602.8 1592.98   612.6  1597.5     632 1608.34   641.7 1613.24
#Mann= 3 ,-1 , 0
       0     .12       0   165.3    .045       0   213.9     .12       0
Bank Sta=165.3,213.9
XS Rating Curve= 0 ,0
Exp/Cntr=0.3,0.1

Type RM Length L Ch R = 1 ,14529.7 ,438.1,474.1,505.6
XS GIS Cut Line= 3
     1845502.451      228542.821      1845739.43      228766.779
     1846214.481      228783.421
#Sta/Elev= 30
       0 1619.28    28.8 1613.23    57.5 1607.55    86.3 1602.67   115.1 1598.09
   153.4 1592.81   172.6 1589.63   182.2 1587.82   201.4 1583.78   239.8 1575.22
   268.5 1570.31   287.7 1565.45   316.5 1557.19   326.1 1554.83   345.5 1551.94
   355.2 1551.12   384.3 1549.75   442.5 1548.36   529.8 1547.27     588 1547.02
   613.1 1547.01   636.5 1547.05   646.2 1547.28   655.9 1548.15   665.6 1549.65
   694.7 1554.74   704.4 1556.67   743.2 1565.53   772.3 1573.38   801.4  1580.5
#Mann= 3 ,-1 , 0
       0     .12       0     588    .045       0   646.2     .12       0
Bank Sta=588,646.2
XS Rating Curve= 0 ,0
Exp/Cntr=0.3,0.1

Type RM Length L Ch R = 1 ,14055.7 ,349.3,395.5,415.1
XS GIS Cut Line= 3
     1845497.242       228561.05     1845710.784      228790.217
     1846025.948      229256.822
#Sta/Elev= 30
       0  1615.6    29.4 1609.16    48.9 1605.24    97.9 1597.46   156.6 1586.07
   195.8 1577.68   234.9  1570.7   244.7 1568.49   254.5 1565.97   283.9 1557.62
   293.7 1555.14   303.4 1553.42   313.2 1552.37     323 1551.63   390.9 1547.51
   410.3 1546.73   429.7 1546.61   536.5 1546.61   623.9  1547.2     653 1546.86
   691.8 1546.91     721 1546.91   730.7 1547.44   740.4 1548.96   750.1 1551.55
   759.8 1554.75   769.5 1557.63   798.6 1563.96   818.1 1567.67   876.3 1576.85
#Mann= 3 ,-1 , 0
       0     .12       0   623.9    .045       0   691.8     .12       0
Bank Sta=623.9,691.8
XS Rating Curve= 0 ,0
Exp/Cntr=0.3,0.1

Type RM Length L Ch R = 1 ,13660.1 ,292.5,302.8,312.4
XS GIS Cut Line= 4
     1845484.222      228566.259     1845635.263      228787.613
     1845653.492      229131.363     1845622.715      229255.534
#Sta/Elev= 30
       0 1615.06    19.1 1610.32    38.3 1605.89   105.3  1592.5   162.7 1578.74
   229.7 1564.08   239.3 1561.24   248.8 1558.15   258.4 1555.49     268 1553.47
   277.8 1552.09   287.6  1551.4   366.3 1547.83   405.7 1546.84   454.8 1546.43
   494.2 1546.34   523.7  1546.5   553.2 1546.79   572.9 1547.68   582.7 1548.53
   592.5 1549.96   602.4 1552.34   612.2 1555.43   641.7 1565.85   651.6 1568.02
   661.4 1569.65   671.2 1572.18   681.1 1575.55   720.5 1591.11   740.1 1599.82
#Mann= 3 ,-1 , 0
       0     .12       0   454.8    .045       0   523.7     .12       0
Bank Sta=454.8,523.7
XS Rating Curve= 0 ,0
Exp/Cntr=0.3,0.1