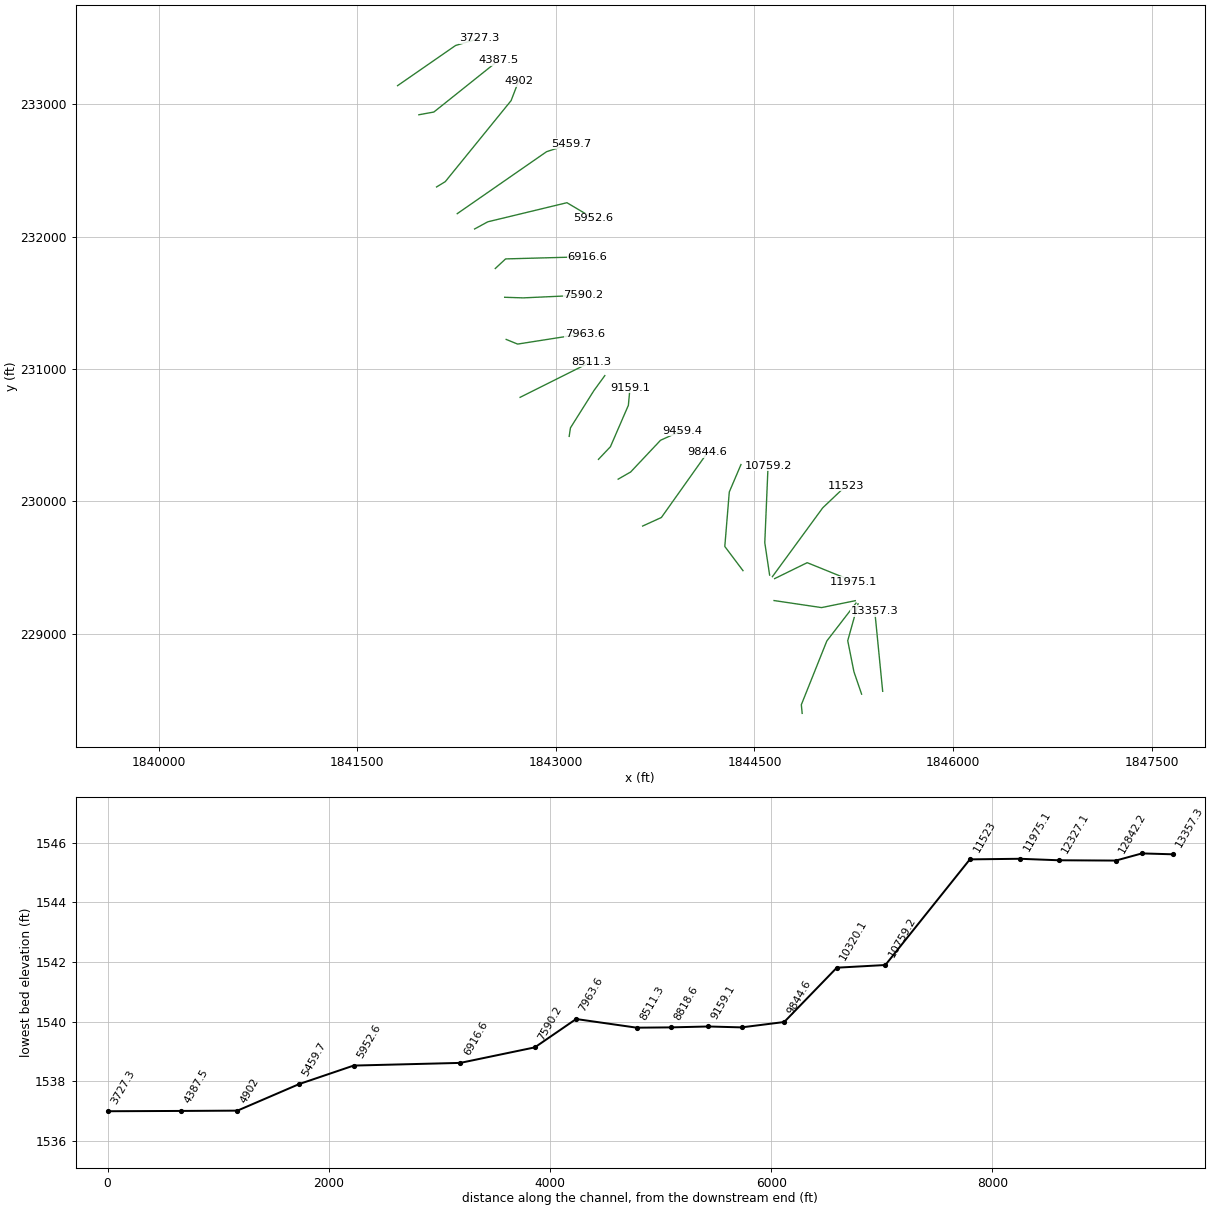
HEC-RAS study GALDECK.prj: GALDECK

--- GALDECK.g01 (geometry) --- (continued)

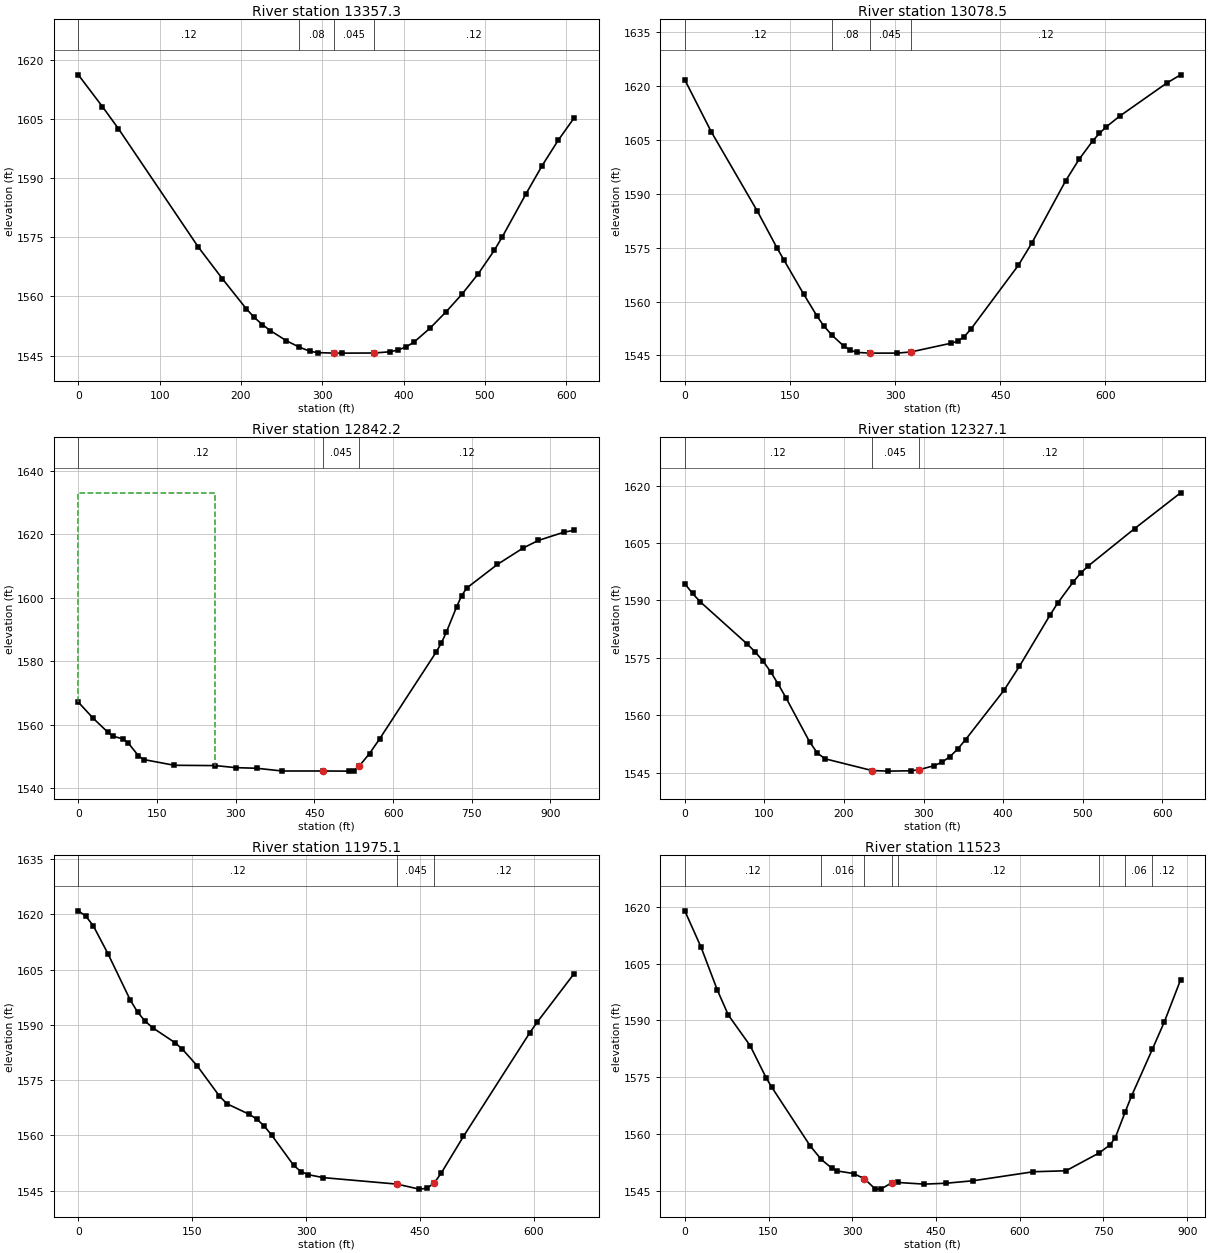
Type RM Length L Ch R = 1 ,13357.3 ,259,278.8,232.4
XS GIS Cut Line= 2
     1845468.597      228566.259     1845408.701      229173.029
#Sta/Elev= 30
       0 1616.31    29.5 1608.26    49.2 1602.66   147.5 1572.56     177 1564.54
   206.5 1556.88   216.4 1554.67   226.2 1552.87     236 1551.34   255.7 1548.78
  271.171547.186   285.2 1546.04     295 1545.73   314.7 1545.62   324.5 1545.61
   363.9 1545.64   383.5 1545.96   393.4 1546.43   403.2  1547.2     413 1548.45
   432.7 1551.99   452.4 1556.15     472 1560.64   491.7 1565.75   511.4 1571.69
   521.2  1575.1   550.7 1586.16   570.4 1593.27     590 1599.66   609.7 1605.38
#Mann= 4 ,-1 , 0
       0     .12       0  271.17     .08       0   314.7    .045       0
   363.9     .12       0
Bank Sta=314.7,363.9
XS Rating Curve= 0 ,0
Exp/Cntr=0.3,0.1

Type RM Length L Ch R = 1 ,13078.5 ,258.9,236.3,232
XS GIS Cut Line= 4
     1845309.318      228544.781     1845251.366      228714.002
     1845204.491      228948.377     1845282.616      229227.022
#Sta/Elev= 30
       0  1621.8    37.7 1607.33   103.6 1585.16   131.8 1574.86   141.2 1571.66
   169.4 1562.13   188.4 1556.03     198 1553.29  209.981550.634   226.7 1547.62
   236.2 1546.44   245.8 1545.84  264.081545.642   264.9 1545.64   303.2 1545.65
   322.3 1545.96   379.6 1548.39   389.2 1548.95   398.8 1550.27   408.3 1552.38
   475.8 1570.11   495.1 1576.32   543.3 1593.66   562.6 1599.68   581.9 1604.77
   591.5 1606.88   601.2 1608.68   620.5 1611.69     688 1620.95   707.3 1623.18
#Mann= 4 ,-1 , 0
       0     .12       0  209.98     .08       0  264.08    .045       0
   322.3     .12       0
Bank Sta=264.08,322.3
XS Rating Curve= 0 ,0
Exp/Cntr=0.3,0.1

Type RM Length L Ch R = 1 ,12842.2 ,545.8,515.1,424.5
XS GIS Cut Line= 4
     1844860.348      228399.449     1844854.013      228464.696
     1845046.722      228946.467     1845266.991      229232.231
#Sta/Elev= 30
       0 1567.13    28.1 1562.09    56.2 1557.67    65.6 1556.46    85.1 1555.53
    94.9 1554.31   114.5 1550.26   124.3 1549.06     183 1547.24   261.4 1547.14
   300.5 1546.49   339.7 1546.31   388.6 1545.44     467 1545.44   515.9  1545.4
   525.7 1545.57   535.5    1547   555.1 1550.94   574.6 1555.62     682 1582.88
   691.7 1585.66   701.4 1589.12     721 1597.12   730.7 1600.69   740.5 1603.12
     799 1610.56   847.7 1615.69     877 1618.11   925.7  1620.7   945.2  1621.3
#Mann= 3 ,-1 , 0
       0     .12       0     467    .045       0   535.5     .12       0
#XS Ineff= 2 , 0
       0     260 1633.11               0
Permanent Ineff=
       F       F
Bank Sta=467,535.5
XS Rating Curve= 0 ,0
Exp/Cntr=0.3,0.1

Type RM Length L Ch R = 1 ,12327.1 ,360.4,352,345.3
XS GIS Cut Line= 3
     1844648.019      229251.569     1845006.574      229198.377
     1845261.782       229250.46
#Sta/Elev= 30
       0 1594.39     9.8 1591.82    19.6 1589.61    78.4 1578.62    88.2 1576.59
      98 1574.26   107.8 1571.38   117.6 1568.06   127.4 1564.46   156.8 1553.07
   166.5 1550.14   176.3 1548.63   235.1 1545.57   254.7 1545.41   284.1  1545.5
   293.9 1545.76   313.5 1546.84   323.3 1547.77   333.1 1549.19   342.9 1551.18
   352.7 1553.62   401.1 1566.54   420.4 1572.78     459 1586.22   468.6 1589.34
   487.9  1594.8   497.5 1597.17   507.2 1599.06   565.1 1608.76     623 1618.12
#Mann= 3 ,-1 , 0
       0     .12       0   235.1    .045       0   293.9     .12       0
Bank Sta=235.1,293.9
XS Rating Curve= 0 ,0
Exp/Cntr=0.3,0.1

Type RM Length L Ch R = 1 ,11975.1 ,380,452.1,483.6
XS GIS Cut Line= 3
     1844652.268      229417.167     1844898.284      229537.613
     1845249.683      229395.274
#Sta/Elev= 30
       0 1620.91     9.8 1619.48    19.6 1616.89    39.1 1609.25    68.5 1596.68
    78.3 1593.37      88    1591    97.8 1589.22   127.2 1585.18     137 1583.41
   156.5  1578.9   185.9 1570.66   195.7  1568.6     225 1565.75   234.8 1564.48
   244.6 1562.61   254.4 1560.17   283.6  1551.9   293.4 1550.18   303.1 1549.37
   322.5 1548.58   419.7 1546.82   448.9 1545.46   458.6 1545.67   468.4 1547.02
   478.1 1549.86   507.2 1559.76   594.7  1587.9   604.4 1590.76     653  1603.9
#Mann= 3 ,-1 , 0
       0     .12       0   419.7    .045       0   468.4     .12       0
Bank Sta=419.7,468.4
XS Rating Curve= 0 ,0
Exp/Cntr=0.3,0.1

Type RM Length L Ch R = 1 ,11523   ,704.5,763.8,764.4
XS GIS Cut Line= 3
     1844635.374       229431.95     1845015.472      229951.675
     1845192.754      230119.866
#Sta/Elev= 30
       0 1618.94    29.3 1609.27    58.5 1597.94      78 1591.41   117.1 1583.32
   146.3 1574.68   156.1 1572.29   224.4 1556.91  244.341553.301   263.4 1550.97
   273.2 1550.23   302.4 1549.56   321.9 1548.17   341.4 1545.44   351.2 1545.44
   370.7 1547.11  381.661547.196   429.3 1546.76   468.3    1547   517.1 1547.66
   624.4 1550.03     683 1550.29  741.861554.954   761.2 1557.05     771 1558.93
  788.871565.773   800.3 1570.02  837.821582.436   858.9 1589.53   888.3 1600.74
#Mann= 8 ,-1 , 0
       0     .12       0  244.34    .016       0   321.9    .045       0
   370.7    .016       0  381.66     .12       0  741.86    .016       0
  788.87     .06       0  837.82     .12       0
Bank Sta=321.9,370.7
XS Rating Curve= 0 ,0
Exp/Cntr=0.3,0.1

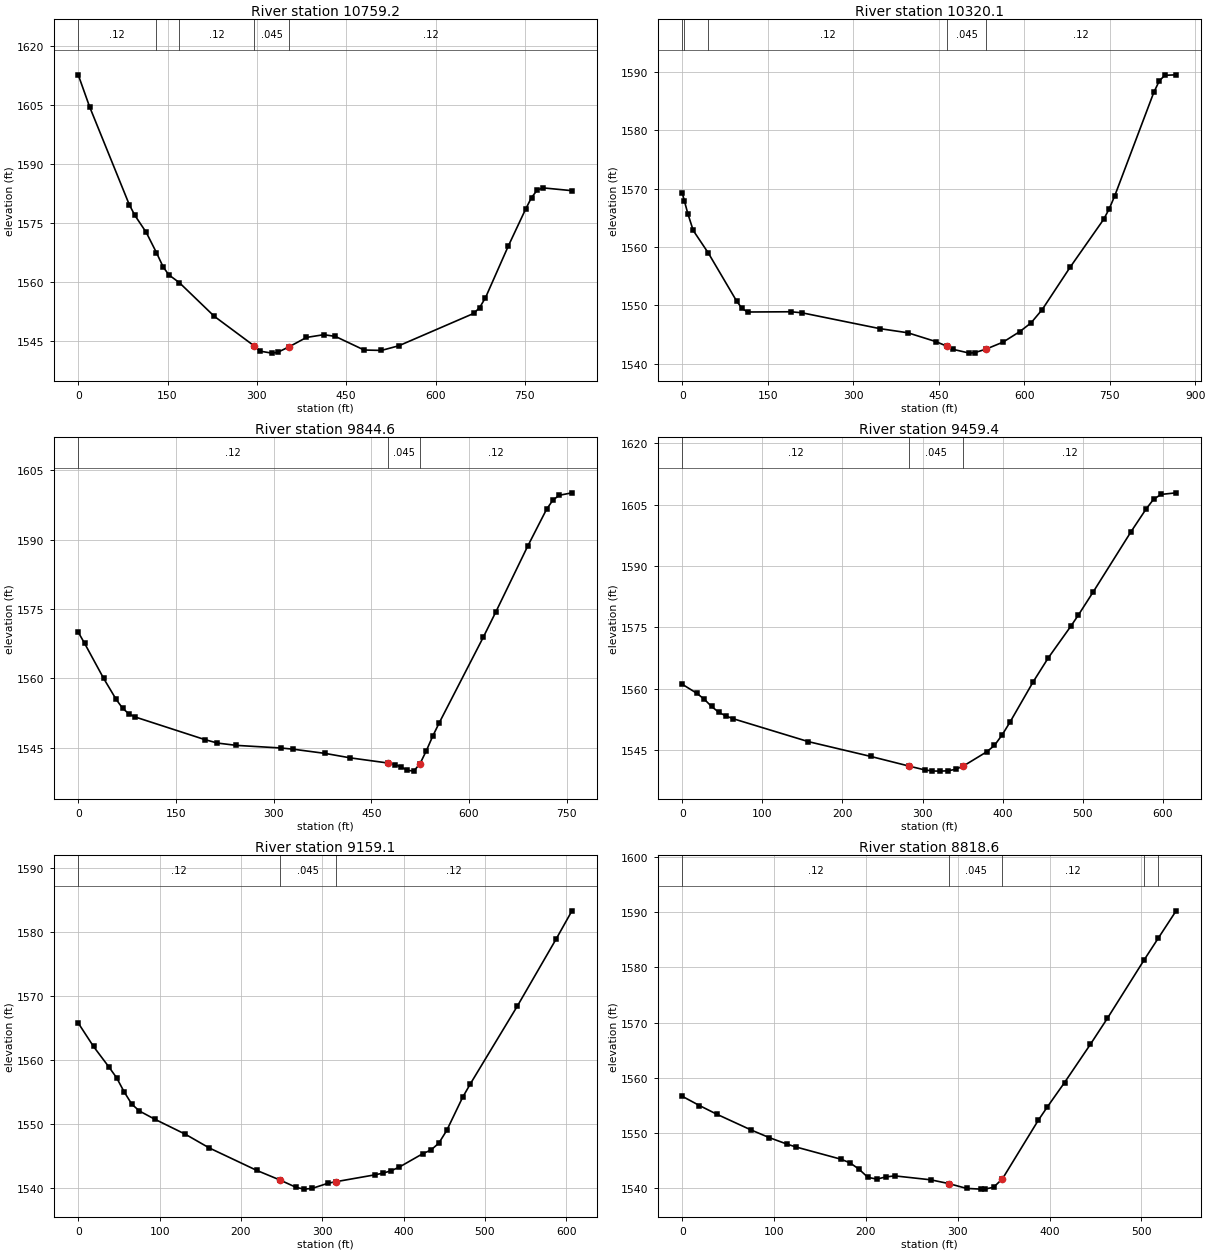
Type RM Length L Ch R = 1 ,10759.2 ,416.5,439.1,438.6
XS GIS Cut Line= 3
      1844614.43      229443.863     1844577.972      229688.654
     1844602.662      230269.707
#Sta/Elev= 30
       0 1612.72      19 1604.63    85.7 1579.69    95.2 1576.93   114.2 1572.63
  131.241567.505   142.8 1563.78   152.3  1561.8  169.871559.827   228.4 1551.28
     296 1543.68   305.6  1542.4     325  1541.9   334.7 1542.09   354.1 1543.51
   383.2 1545.89   412.3 1546.59   431.7 1546.16   480.1 1542.69   509.2 1542.59
   538.3 1543.77   664.3 1552.02     674 1553.49   683.7 1555.94   722.4 1569.22
   751.5 1578.61   761.2 1581.49   770.9 1583.42   780.6 1583.95   829.1 1583.24
#Mann= 5 ,-1 , 0
       0     .12       0  131.24    .016       0  169.87     .12       0
     296    .045       0   354.1     .12       0
Bank Sta=296,354.1
XS Rating Curve= 0 ,0
Exp/Cntr=0.3,0.1

Type RM Length L Ch R = 1 ,10320.1 ,489.6,475.5,444.8
XS GIS Cut Line= 4
     1844413.296      229477.426     1844275.888      229660.009
     1844309.742      230071.467     1844398.068      230278.693
#Sta/Elev= 30
       0 1569.18    3.611567.869     9.5 1565.73      19 1562.84   45.521558.968
    95.2 1550.73   104.7 1549.47   114.3 1548.86   190.4  1548.9   209.5 1548.73
   346.5 1546.01   395.6  1545.3   444.8 1543.79   464.4 1542.99   474.2 1542.48
   503.7 1541.81   513.6  1541.9   533.2 1542.51   562.7 1543.69   592.2  1545.5
   611.9 1546.99   631.5 1549.27   680.5 1556.53   739.3 1564.73   749.1 1566.53
   758.9 1568.79   827.4 1586.51   837.2 1588.51     847 1589.44   866.6 1589.52
#Mann= 5 ,-1 , 0
       0     .12       0    3.61    .016       0   45.52     .12       0
   464.4    .045       0   533.2     .12       0
Bank Sta=464.4,533.2
XS Rating Curve= 0 ,0
Exp/Cntr=0.3,0.1

Type RM Length L Ch R = 1 ,9844.6  ,392.4,385.2,372.7
XS GIS Cut Line= 3
     1843655.193      229814.323     1843796.722      229878.759
     1844145.564      230370.094
#Sta/Elev= 30
       0    1570     9.7 1567.61    38.9 1560.05    58.3 1555.47      68  1553.6
    77.8 1552.34    87.5 1551.68   194.4  1546.8   213.8 1546.05     243 1545.55
     311 1544.99   330.4 1544.72     379 1543.82   417.9 1542.85   476.2 1541.73
     486 1541.42   495.7 1540.89   505.4 1540.17   515.1 1539.99   524.8 1541.59
   534.6 1544.43   544.3 1547.54     554 1550.34     622 1568.93   641.5 1574.46
     690 1588.54   719.2 1596.57   728.9 1598.53   738.6 1599.57   758.1  1600.1
#Mann= 3 ,-1 , 0
       0     .12       0   476.2    .045       0   524.8     .12       0
Bank Sta=476.2,524.8
XS Rating Curve= 0 ,0
Exp/Cntr=0.3,0.1

Type RM Length L Ch R = 1 ,9459.4  ,285.2,300.3,318.6
XS GIS Cut Line= 4
     1843470.123      230168.354     1843564.734      230222.682
     1843790.428      230462.265     1843953.064        230535.9
#Sta/Elev= 30
       0 1561.05    18.2 1558.83    27.3 1557.41    36.4 1555.63    45.5 1554.21
    54.6 1553.29    63.6 1552.62   157.5 1547.02     235 1543.42   283.4 1541.03
   302.7 1540.11   312.4 1539.84   322.1 1539.81   331.8 1539.89   341.4 1540.26
   351.1 1541.07   380.2 1544.54   389.8 1546.09   399.5 1548.69   409.2 1551.78
   438.2 1561.66     457  1567.5   485.2 1575.25   494.6 1577.98   513.4 1583.72
   560.4 1598.38   579.2 1603.93   588.6 1606.32     598 1607.52   616.8 1607.91
#Mann= 3 ,-1 , 0
       0     .12       0   283.4    .045       0   351.1     .12       0
Bank Sta=283.4,351.1
XS Rating Curve= 0 ,0
Exp/Cntr=0.3,0.1

Type RM Length L Ch R = 1 ,9159.1  ,345.9,340.5,334.6
XS GIS Cut Line= 4
     1843321.341       230317.89     1843411.956      230413.654
     1843547.373      230726.154     1843559.829      230860.055
#Sta/Elev= 30
       0  1565.8    18.8 1562.13    37.7 1558.93    47.1 1557.26    56.5 1555.03
    65.9 1553.11    75.3 1552.04    94.2 1550.76   131.8 1548.41     161 1546.28
   219.4 1542.77   248.6 1541.23   268.1  1540.1   277.8 1539.84   287.5 1539.95
     307 1540.76   316.7    1541   365.4 1542.09   375.1 1542.35   384.8 1542.72
   394.6 1543.28   423.8  1545.4   433.5 1545.94   443.2 1547.02     453 1549.02
   472.4 1554.16     482 1556.29   539.7 1568.43   587.7 1578.98   606.9 1583.33
#Mann= 3 ,-1 , 0
       0     .12       0   248.6    .045       0   316.7     .12       0
Bank Sta=248.6,316.7
XS Rating Curve= 0 ,0
Exp/Cntr=0.3,0.1

Type RM Length L Ch R = 1 ,8818.6  ,327.9,307.3,281.2
XS GIS Cut Line= 4
     1843100.193      230491.486     1843109.873      230556.015
     1843286.956      230837.265      1843369.53       230950.63
#Sta/Elev= 29
       0 1556.62    18.6 1554.96    37.3  1553.4      75 1550.52    94.6 1549.15
   114.1 1547.96   123.9 1547.44   172.8 1545.23   182.6 1544.57   192.3 1543.44
   202.1 1541.94   211.9 1541.63   221.6 1542.02   231.4 1542.21   270.5  1541.5
   290.1 1540.82   309.6 1539.94   325.4 1539.81   329.2 1539.81     339 1540.14
   348.7 1541.69   387.8 1552.31   397.6 1554.71   416.3 1559.12   444.4 1566.03
   463.1 1570.79  503.031581.346   518.41585.287   537.9 1590.25
#Mann= 5 ,-1 , 0
       0     .12       0   290.1    .045       0   348.7     .12       0
  503.03     .06       0   518.4     .12       0
Bank Sta=290.1,348.7
XS Rating Curve= 0 ,0
Exp/Cntr=0.3,0.1

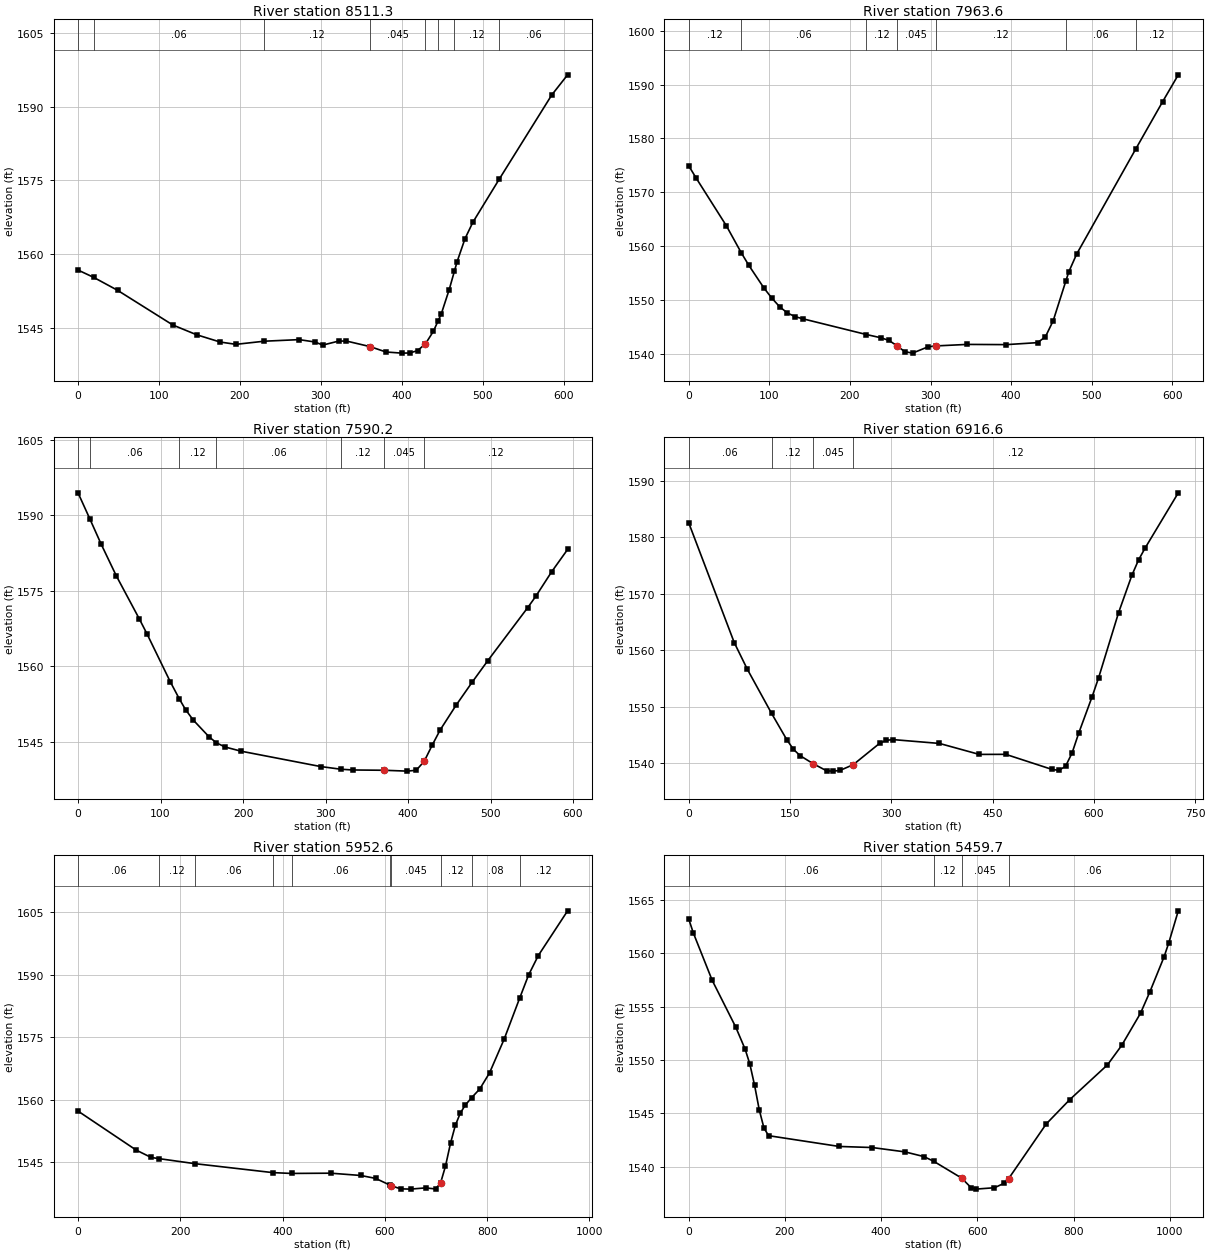
Type RM Length L Ch R = 1 ,8511.3  ,516.2,547.7,404.1
XS GIS Cut Line= 2
     1842729.365      230786.487     1843270.413       231057.01
#Sta/Elev= 30
       0 1556.72    19.2 1555.24    48.8  1552.6   117.1 1545.53   146.4 1543.55
   175.6 1542.06   195.1 1541.59   230.2 1542.23   273.2 1542.55   292.7 1542.07
   302.4 1541.44     322 1542.25   331.7 1542.26     361 1541.12   380.5 1540.03
     400  1539.8   409.8 1539.83   419.5 1540.31   429.3  1541.7     439 1544.23
  444.921546.375   448.8 1547.78   458.6 1552.74  465.131556.544   468.3 1558.39
   478.1  1563.1   487.8 1566.44  520.331575.204   585.4  1592.4   604.9 1596.48
#Mann= 8 ,-1 , 0
       0     .12       0    19.2     .06       0   230.2     .12       0
     361    .045       0   429.3     .12       0  444.92     .06       0
  465.13     .12       0  520.33     .06       0
Bank Sta=361,429.3
XS Rating Curve= 0 ,0
Exp/Cntr=0.3,0.1

Type RM Length L Ch R = 1 ,7963.6  ,377.3,373.4,369.7
XS GIS Cut Line= 3
     1842624.215       231223.72     1842710.784      231188.654
     1843218.339       231268.22
#Sta/Elev= 30
       0 1574.92     9.3 1572.62    46.7 1563.77   65.121558.768    74.7 1556.38
    93.4 1552.18   103.1 1550.32   112.8 1548.71   122.5 1547.55   132.2 1546.86
   141.9 1546.46  220.411543.547   238.8 1542.93   248.5 1542.44   258.2 1541.47
   267.9 1540.37   277.6 1540.09     297 1541.27   306.7 1541.43   345.4 1541.71
   393.9 1541.67   432.7 1542.04   442.4 1543.12   452.1 1546.12  467.911553.565
   471.4 1555.19   481.1 1558.48  554.421578.025   587.8 1586.83   607.2 1591.82
#Mann= 7 ,-1 , 0
       0     .12       0   65.12     .06       0  220.41     .12       0
   258.2    .045       0   306.7     .12       0  467.91     .06       0
  554.42     .12       0
Bank Sta=258.2,306.7
XS Rating Curve= 0 ,0
Exp/Cntr=0.3,0.1

Type RM Length L Ch R = 1 ,7590.2  ,588.4,673.6,622.1
XS GIS Cut Line= 3
     1842612.905      231542.114     1842752.451      231537.613
      1843205.73      231558.216
#Sta/Elev= 30
       0 1594.49   14.231589.342    27.9 1584.33    46.5 1577.95    74.5 1569.35
    83.8 1566.37   111.7 1556.95  122.851553.487   130.3 1551.38   139.6 1549.31
   158.9 1545.95  167.811544.765   178.2 1543.94   197.5 1543.11   294.1 1540.05
  318.241539.524   332.7 1539.37   371.3 1539.31     399 1539.14   409.9 1539.31
   419.6 1541.09   429.2 1544.28   438.9 1547.32   458.2 1552.24   477.5 1556.78
   496.8 1561.14   545.1 1571.67   554.8  1573.9   574.1  1578.8   593.4 1583.23
#Mann= 7 ,-1 , 0
       0     .12       0   14.23     .06       0  122.85     .12       0
  167.81     .06       0  318.24     .12       0   371.3    .045       0
   419.6     .12       0
Bank Sta=371.3,419.6
XS Rating Curve= 0 ,0
Exp/Cntr=0.3,0.1

Type RM Length L Ch R = 1 ,6916.6  ,869,964,951.6
XS GIS Cut Line= 3
     1842542.098      231759.464     1842619.638      231831.884
     1843238.416      231848.708
#Sta/Elev= 30
       0 1582.58    67.5 1561.36    86.8 1556.66  122.771548.837   145.4 1544.16
   155.2 1542.47     165 1541.36   184.7 1539.91   204.4 1538.67   213.8 1538.62
     224 1538.74   243.7 1539.76     283 1543.56   292.8 1544.07   302.6  1544.2
   371.4 1543.52   430.3 1541.58   469.6 1541.59   538.4 1538.91   548.2 1538.76
   558.1 1539.47   567.9 1541.86   577.7 1545.36   597.4 1551.76   607.2 1555.18
   636.7 1566.67   656.3 1573.25   666.2 1575.98     676  1578.1   725.1 1587.87
#Mann= 4 ,-1 , 0
       0     .06       0  122.77     .12       0   184.7    .045       0
   243.7     .12       0
Bank Sta=184.7,243.7
XS Rating Curve= 0 ,0
Exp/Cntr=0.3,0.1

Type RM Length L Ch R = 1 ,5952.6  ,527.7,492.9,511.2
XS GIS Cut Line= 4
     1842385.676      232058.051     1842485.703      232112.204
      1843083.18      232256.363     1843280.278      232139.787
#Sta/Elev= 30
       0 1557.28   113.7 1547.91     143 1546.14  158.911545.846  228.191544.654
  381.011542.495  417.57  1542.3   494.2 1542.36   552.8 1541.81     582 1541.11
  609.161539.538   611.3 1539.39   630.8  1538.6   650.3 1538.53   679.6 1538.83
   699.1 1538.57   708.9 1539.98   718.6 1544.06   728.4 1549.55   737.9 1553.87
   747.4 1556.74     757 1558.67  769.791560.521   785.6 1562.58   804.7 1566.45
   833.3 1574.56  863.431584.345     881 1589.95   900.1 1594.65   957.4 1605.39
#Mann= 10 ,-1 , 0
       0     .06       0  158.91     .12       0  228.19     .06       0
  381.01     .12       0  417.57     .06       0  609.16     .12       0
   611.3    .045       0   708.9     .12       0  769.79     .08       0
  863.43     .12       0
Bank Sta=611.3,708.9
XS Rating Curve= 0 ,0
Exp/Cntr=0.3,0.1

Type RM Length L Ch R = 1 ,5459.7  ,533.5,557.7,526.7
XS GIS Cut Line= 3
     1842254.513      232173.653     1842929.534      232641.779
     1843116.125      232702.579
#Sta/Elev= 30
       0 1563.24     9.8 1561.91    48.9 1557.48    97.8  1553.1   117.4 1551.02
   127.1 1549.64   136.9 1547.66   146.7 1545.34   156.5 1543.63   166.2 1542.92
   312.9 1541.91   381.4 1541.81   449.8  1541.4     489 1540.96  509.341540.519
   567.2 1538.95   586.8 1538.06   596.5 1537.91   635.6 1538.04   655.2 1538.45
     665 1538.89   743.2 1544.02   792.1  1546.3   870.5 1549.56     900 1551.38
   939.2  1554.4   958.8 1556.42   988.3  1559.7   998.1 1561.02  1017.7    1564
#Mann= 4 ,-1 , 0
       0     .06       0  509.34     .12       0   567.2    .045       0
     665     .06       0
Bank Sta=567.2,665
XS Rating Curve= 0 ,0
Exp/Cntr=0.3,0.1

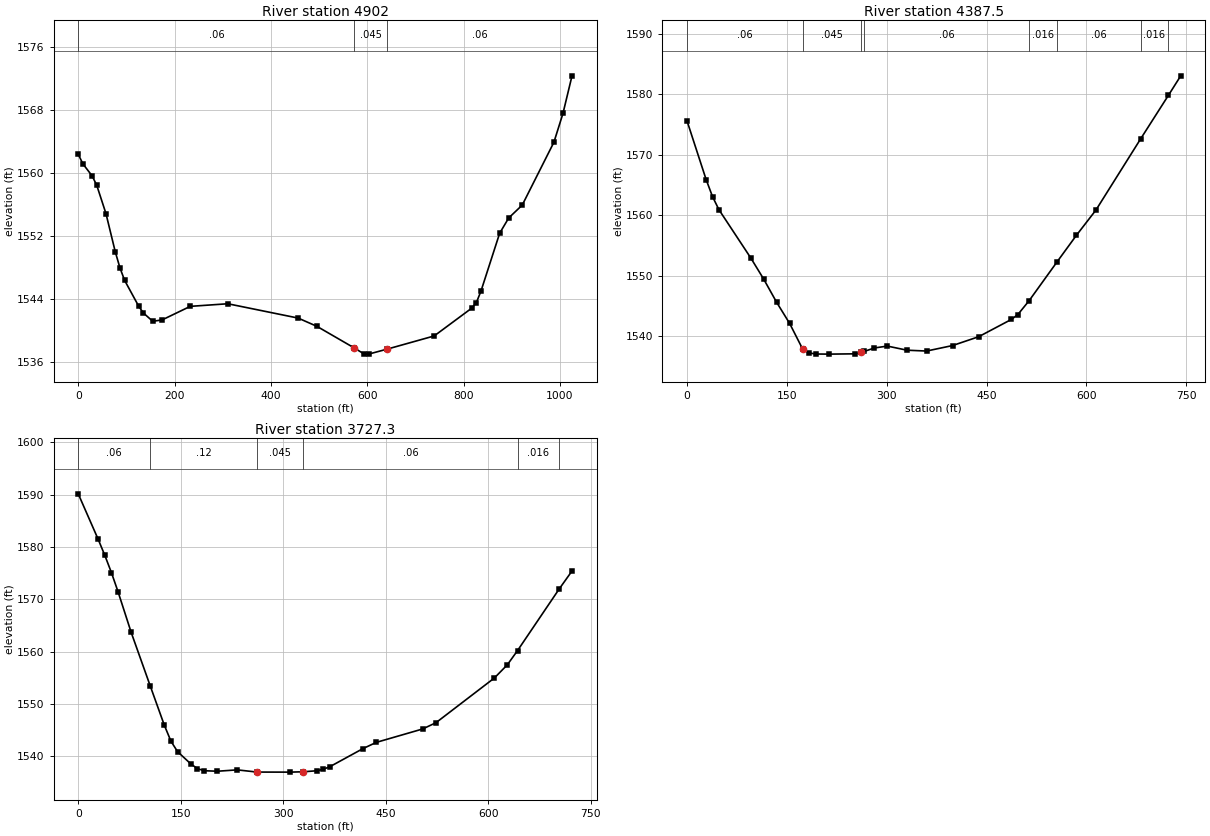
Type RM Length L Ch R = 1 ,4902    ,504.9,514.6,460.9
XS GIS Cut Line= 4
      1842098.21      232375.427     1842163.909      232415.217
     1842661.305      233027.196     1842718.779      233176.013
#Sta/Elev= 30
       0 1562.42     9.6  1561.2    28.8 1559.67    38.4 1558.48    57.6 1554.87
    76.8 1550.04    86.6 1547.98    96.3 1546.39   125.5 1543.11   135.2 1542.25
   154.7 1541.19   174.2 1541.37   232.6 1543.09   310.5 1543.42   456.5  1541.6
   495.5 1540.55   573.4 1537.79   592.8 1537.06   602.6 1537.02   641.5 1537.66
   738.9 1539.33   816.8 1542.86   826.5 1543.57   836.2 1545.06   874.8 1552.38
   893.6 1554.32   921.7 1555.96   987.4 1563.94  1006.2  1567.6    1025 1572.38
#Mann= 3 ,-1 , 0
       0     .06       0   573.4    .045       0   641.5     .06       0
Bank Sta=573.4,641.5
XS Rating Curve= 0 ,0
Exp/Cntr=0.3,0.1

Type RM Length L Ch R = 1 ,4387.5  ,405.2,660.1,467
XS GIS Cut Line= 3
     1841964.717      232920.667     1842077.972      232941.259
     1842567.607      233332.208
#Sta/Elev= 30
       0 1575.64    28.8  1565.9    38.4 1563.08      48 1560.92    95.9 1552.92
   115.1 1549.46   134.7 1545.59   154.3 1542.08   173.8 1537.85   183.6 1537.21
   193.4 1537.03     213 1537.01   252.2 1537.06     262 1537.29  266.541537.466
   281.5 1538.03   301.1 1538.34   330.5 1537.66   359.9 1537.52     399 1538.43
   438.2 1539.89   487.1 1542.74   496.9 1543.54  514.161545.881  556.29 1552.33
     585 1556.67   614.4 1560.86  681.491572.631  723.071579.808   741.7 1583.06
#Mann= 8 ,-1 , 0
       0     .06       0   173.8    .045       0     262     .12       0
  266.54     .06       0  514.16    .016       0  556.29     .06       0
  681.49    .016       0  723.07     .06       0
Bank Sta=173.8,262
XS Rating Curve= 0 ,0
Exp/Cntr=0.3,0.1

Type RM Length L Ch R = 1 ,3727.3  ,590.5,568.8,579.8
XS GIS Cut Line= 3
     1841803.859      233140.386     1842242.034      233443.863
       1842423.6      233497.842
#Sta/Elev= 30
       0 1590.13    29.1 1581.47    38.8 1578.42    48.5 1575.11    58.2 1571.46
    77.5 1563.66  105.211553.502     126 1545.94   135.7 1542.89   145.4  1540.9
   164.8 1538.56   174.4 1537.67   184.1 1537.27   203.5 1537.17   232.6 1537.43
   261.7 1537.01   310.1    1537   329.5 1537.07   348.9 1537.26   358.6 1537.55
   368.3 1538.05   416.7  1541.5   436.1 1542.68   503.9 1545.24   523.3 1546.43
   608.8 1554.97   627.7 1557.48  642.781560.219  703.441571.929   722.4  1575.4
#Mann= 6 ,-1 , 0
       0     .06       0  105.21     .12       0   261.7    .045       0
   329.5     .06       0  642.78    .016       0  703.44     .06       0
Bank Sta=261.7,329.5
XS Rating Curve= 0 ,0
Exp/Cntr=0.3,0.1