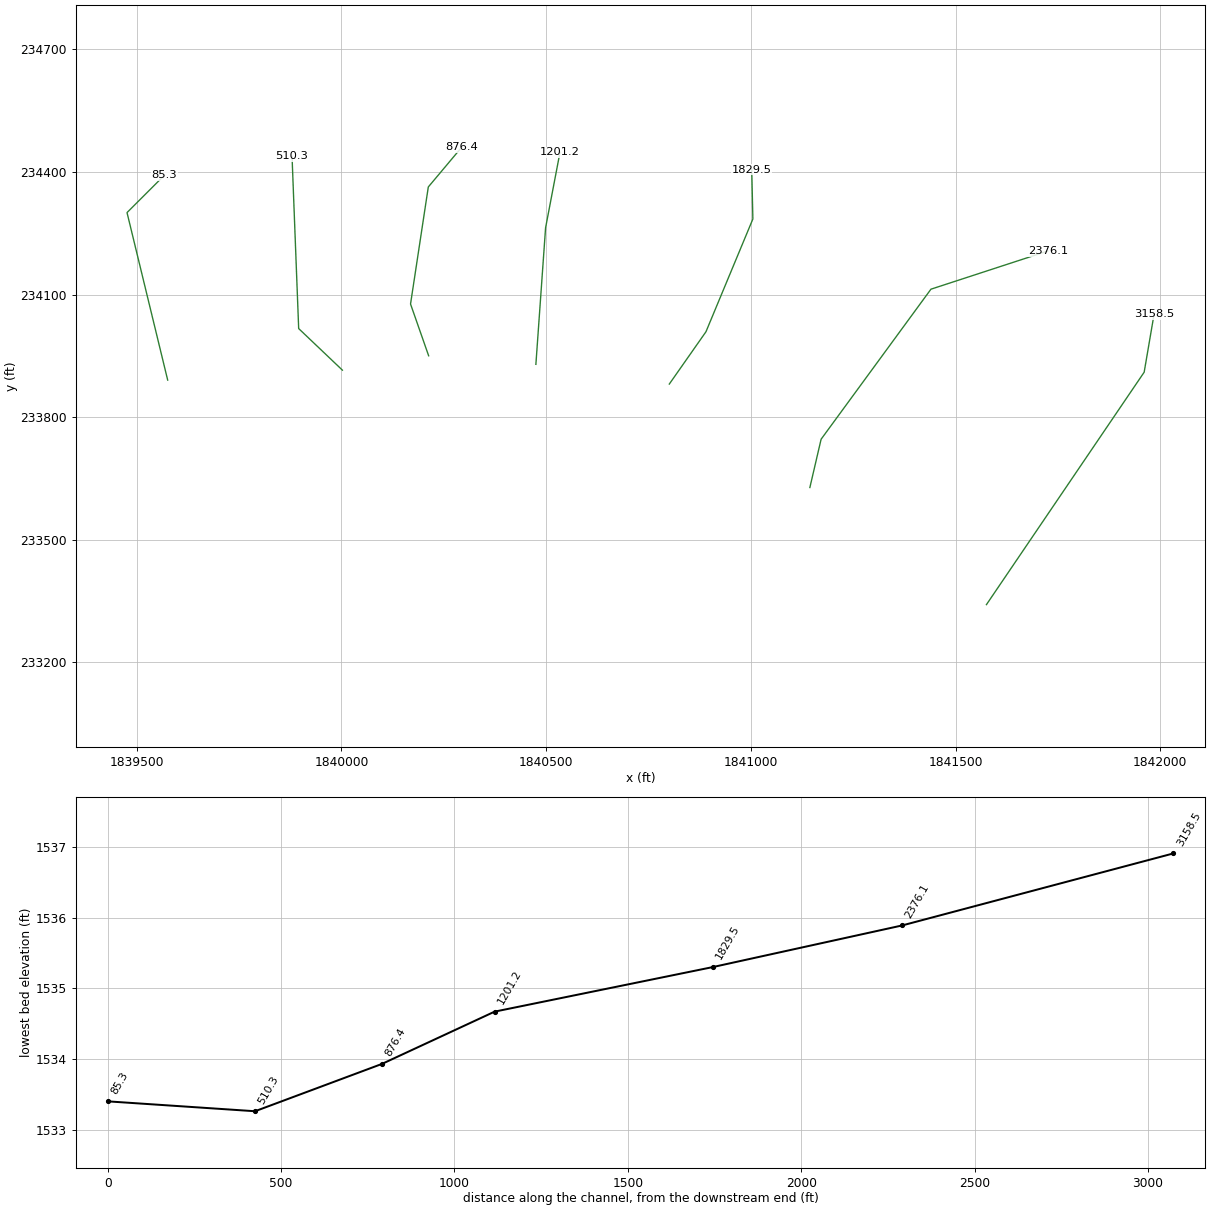
HEC-RAS study GALDECK.prj: GALDECK

--- GALDECK.g01 (geometry) --- (continued)

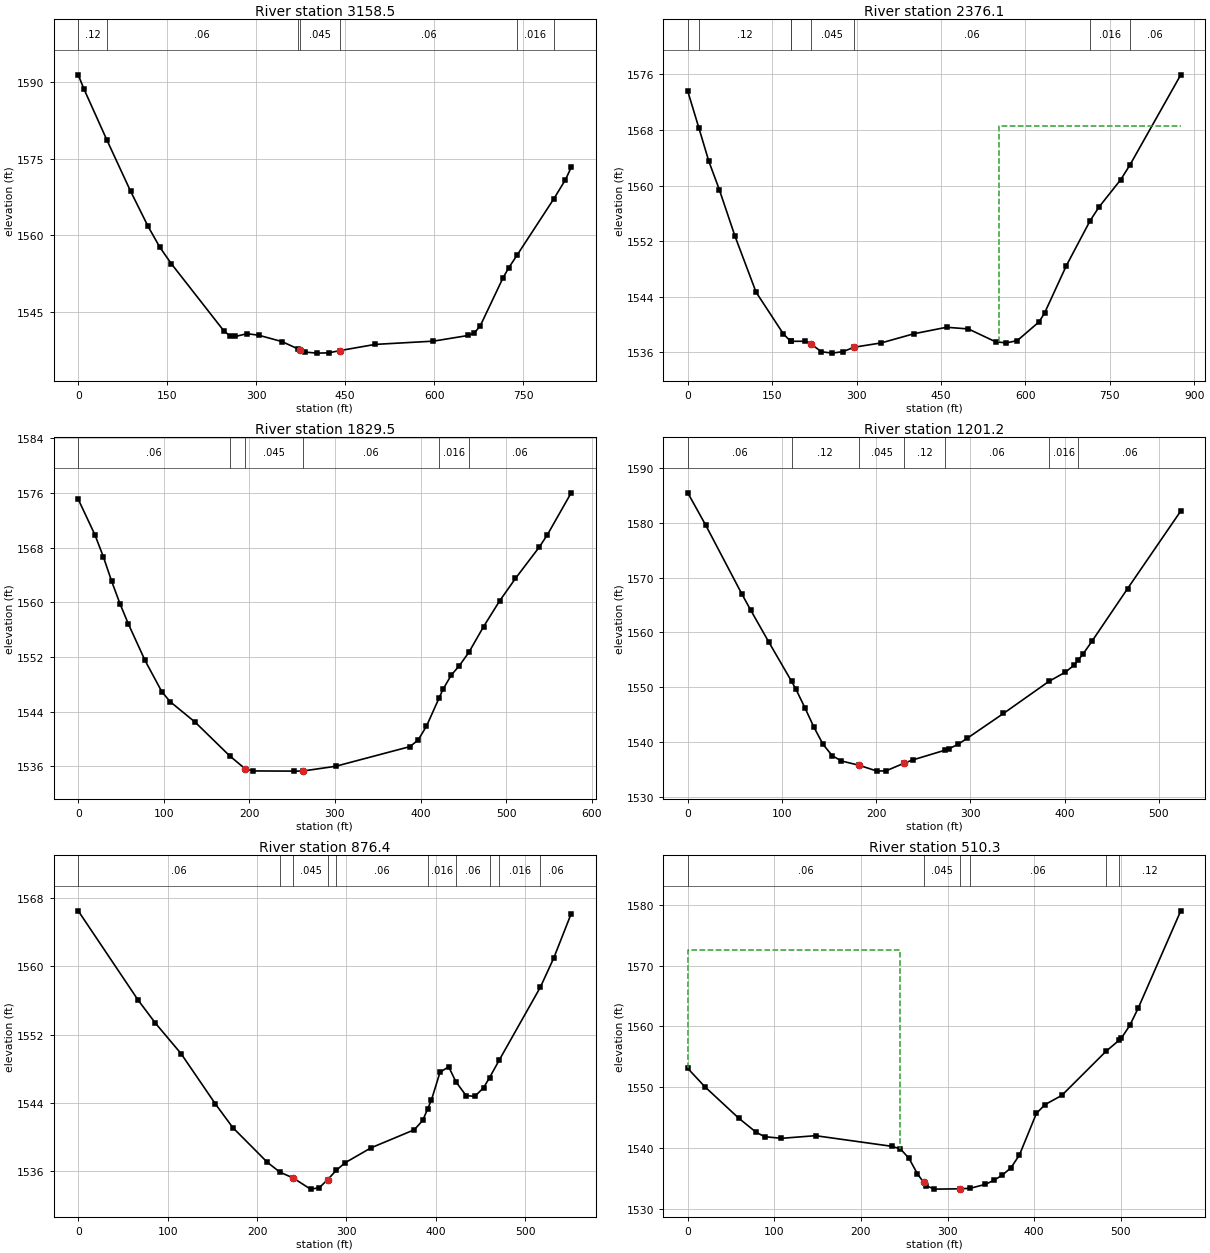
Type RM Length L Ch R = 1 ,3158.5  ,758.1,782.4,775
XS GIS Cut Line= 3
     1841575.555      233341.167     1841960.784      233910.009
     1841984.953      234051.727
#Sta/Elev= 30
       0 1591.47     9.8 1588.66   48.331578.698    88.3 1568.65   117.8 1561.75
   137.4  1557.7     157 1554.43   245.4 1541.28   255.2 1540.34     265 1540.18
   284.6 1540.72   304.2 1540.42   343.5 1539.17  369.741537.771     373 1537.59
   382.8 1537.11   402.4 1536.91     422 1536.96   441.6 1537.42   500.5 1538.62
   598.7 1539.26   657.6 1540.38   667.4 1540.87   677.2 1542.17   715.8 1551.64
   725.4 1553.61  739.491556.099  801.511567.155   821.2 1570.92   830.8 1573.32
#Mann= 7 ,-1 , 0
       0     .12       0   48.33     .06       0  369.74     .12       0
     373    .045       0   441.6     .06       0  739.49    .016       0
  801.51     .06       0
Bank Sta=373,441.6
XS Rating Curve= 0 ,0
Exp/Cntr=0.3,0.1

Type RM Length L Ch R = 1 ,2376.1  ,534.1,546.6,535.3
XS GIS Cut Line= 4
     1841144.242      233627.701     1841171.722      233745.946
     1841439.951      234113.134     1841725.182       234206.45
#Sta/Elev= 30
       0 1573.57   19.85 1568.26    37.4  1563.5      56 1559.43      84  1552.7
   121.4 1544.66   169.8 1538.67  182.691537.602  183.241537.587   208.5  1537.6
   218.2 1537.26   237.5 1536.09   256.8 1535.89   276.2 1536.11   295.6 1536.74
   343.9 1537.36     402 1538.68     460 1539.61   498.7 1539.37   547.1 1537.52
   566.4 1537.36   585.8  1537.7   624.5  1540.4   634.2 1541.67   672.9 1548.48
  715.191554.958     731 1556.92   769.7 1560.87  785.671562.936   876.2 1575.93
#Mann= 8 ,-1 , 0
       0     .06       0   19.85     .12       0  182.69     .06       0
  183.24     .12       0   218.2    .045       0   295.6     .06       0
  715.19    .016       0  785.67     .06       0
#XS Ineff= 2 , 0
                          552.33         1568.58
Permanent Ineff=
       F       F
Bank Sta=218.2,295.6
XS Rating Curve= 0 ,0
Exp/Cntr=0.3,0.1

Type RM Length L Ch R = 1 ,1829.5  ,574,628.3,605.7
XS GIS Cut Line= 4
      1840800.96      233880.965     1840890.472      234008.967
     1841005.055      234285.009     1841002.265      234405.901
#Sta/Elev= 30
       0 1575.11    19.5 1569.91    29.3 1566.71      39 1563.13    48.8 1559.81
    58.6 1556.85    78.1  1551.5    97.6 1546.95   107.4 1545.47   136.7 1542.46
   177.11537.523   194.8 1535.67   204.4 1535.33   252.6  1535.3   262.2 1535.31
   300.8 1536.01   387.6 1538.89   397.2 1539.86   406.9 1541.87   421.81546.045
   426.2 1547.27   435.8 1549.34   445.4 1550.75  456.461552.694   473.7 1556.47
   492.3  1560.2   510.9 1563.51   538.8 1568.11   548.1 1569.88     576 1576.04
#Mann= 6 ,-1 , 0
       0     .06       0   177.1     .12       0   194.8    .045       0
   262.2     .06       0   421.8    .016       0  456.46     .06       0
Bank Sta=194.8,262.2
XS Rating Curve= 0 ,0
Exp/Cntr=0.3,0.1

Type RM Length L Ch R = 1 ,1201.2  ,326.3,324.8,323.8
XS GIS Cut Line= 3
     1840475.068      233929.232     1840498.762      234263.481
     1840533.988      234448.417
#Sta/Elev= 30
       0 1585.47    19.2 1579.52    57.4 1567.01      67    1564    86.2 1558.18
  110.161551.071   114.9  1549.6   124.5 1546.19     134 1542.67   143.6 1539.57
   153.2 1537.52   162.8 1536.54   181.9 1535.74     201 1534.67   210.6 1534.73
   229.8 1536.13   239.4 1536.74  272.611538.466   277.6 1538.76   287.2  1539.6
   296.8 1540.68   335.1 1545.19  383.381551.047     401 1552.75   410.4 1554.05
   414.51554.935   419.8 1556.08   429.2  1558.4   466.9 1567.98   523.4 1582.15
#Mann= 7 ,-1 , 0
       0     .06       0  110.16     .12       0   181.9    .045       0
   229.8     .12       0  272.61     .06       0  383.38    .016       0
   414.5     .06       0
Bank Sta=181.9,229.8
XS Rating Curve= 0 ,0
Exp/Cntr=0.3,0.1

Type RM Length L Ch R = 1 ,876.4   ,357.1,366,344.2
XS GIS Cut Line= 4
     1840213.153      233950.126       1840168.9      234076.849
     1840212.303      234363.307     1840294.074      234460.904
#Sta/Elev= 30
       0  1566.5    67.1 1556.04    86.3 1553.36     115 1549.79   153.5 1543.89
   172.9 1541.13   211.5 1537.07  225.68 1535.91   240.5 1535.23   259.8 1533.93
   269.4 1534.08   279.1 1535.05  288.411536.115   298.4 1537.01   327.4 1538.76
   375.7 1540.87   385.3 1541.97  390.831543.333     395 1544.36   404.6 1547.61
   414.3 1548.25  422.371546.495   433.8 1544.87   443.5 1544.79   453.3 1545.79
  459.951546.971  470.931549.048  516.741557.546   531.7 1560.95   551.3 1566.17
#Mann= 10 ,-1 , 0
       0     .06       0  225.68     .12       0   240.5    .045       0
   279.1     .12       0  288.41     .06       0  390.83    .016       0
  422.37     .06       0  459.95     .12       0  470.93    .016       0
  516.74     .06       0
Bank Sta=240.5,279.1
XS Rating Curve= 0 ,0
Exp/Cntr=0.3,0.1

Type RM Length L Ch R = 1 ,510.3   ,414.2,425,452.1
XS GIS Cut Line= 3
     1840002.524      233914.975      1839895.68      234016.779
     1839879.477      234438.054
#Sta/Elev= 30
       0  1553.1    19.7 1550.09      59  1544.9    78.7 1542.63    88.6 1541.88
   108.2 1541.61   147.6 1542.04   235.8 1540.29   245.6 1539.86   255.4 1538.32
   265.2 1535.77  272.351534.355     275 1533.83   284.8 1533.26   314.2 1533.31
  326.24  1533.4   343.7 1534.05   353.5 1534.71   363.3 1535.58   373.1 1536.76
   382.9 1538.86   402.5 1545.69   412.3 1547.13   431.9 1548.67  482.821555.901
  498.271557.751   500.5 1558.04   510.3 1560.15   520.1 1563.01   569.2 1578.99
#Mann= 6 ,-1 , 0
       0     .06       0  272.35    .045       0   314.2     .12       0
  326.24     .06       0  482.82    .016       0  498.27     .12       0
#XS Ineff= 2 , 0
          245.15  1572.6
Permanent Ineff=
       F       F
Bank Sta=272.35,314.2
XS Rating Curve= 0 ,0
Exp/Cntr=0.3,0.1

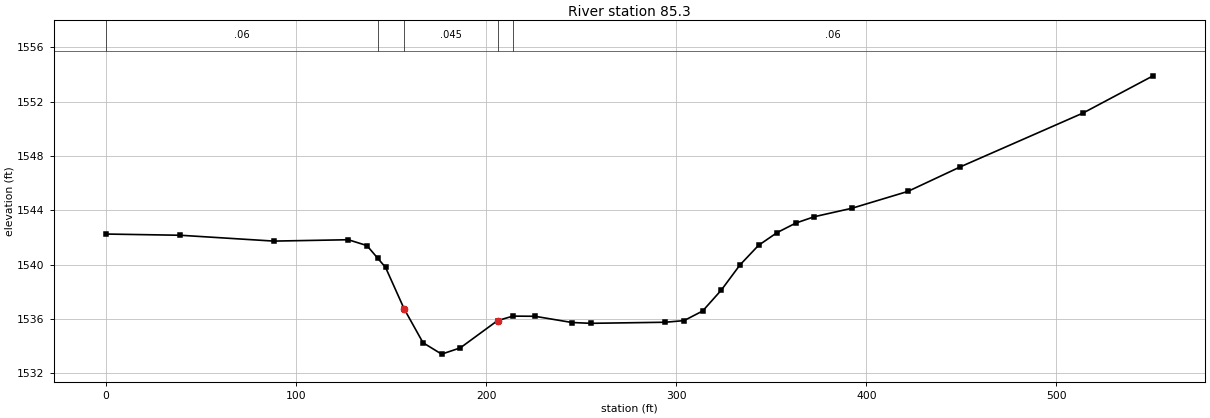
Type RM Length L Ch R = 1 ,85.3    ,92.9,85.3,75.5
XS GIS Cut Line= 3
     1839575.722      233890.704     1839476.409      234300.634
     1839567.666      234391.891
#Sta/Elev= 30
       0 1542.25    39.2 1542.16    88.3 1541.73   127.5 1541.83   137.3  1541.4
   142.9 1540.48   147.1 1539.79   156.9 1536.73   166.8 1534.24   176.6  1533.4
   186.4 1533.86     206 1535.87  214.121536.201   225.6 1536.19   245.2 1535.73
     255 1535.67   294.3 1535.75   304.1 1535.87   313.9 1536.58   323.7 1538.12
   333.5 1539.97   343.3 1541.42   353.1 1542.36   362.9 1543.06   372.7 1543.53
   392.4 1544.15   421.8 1545.39   449.4  1547.2     514 1551.17   550.8 1553.91
#Mann= 5 ,-1 , 0
       0     .06       0   142.9     .12       0   156.9    .045       0
     206     .12       0  214.12     .06       0
Bank Sta=156.9,206
XS Rating Curve= 0 ,0
Exp/Cntr=0.3,0.1

Chan Stop Cuts=-1
Use User Specified Reach Order=0
Composite Channel Slope=5